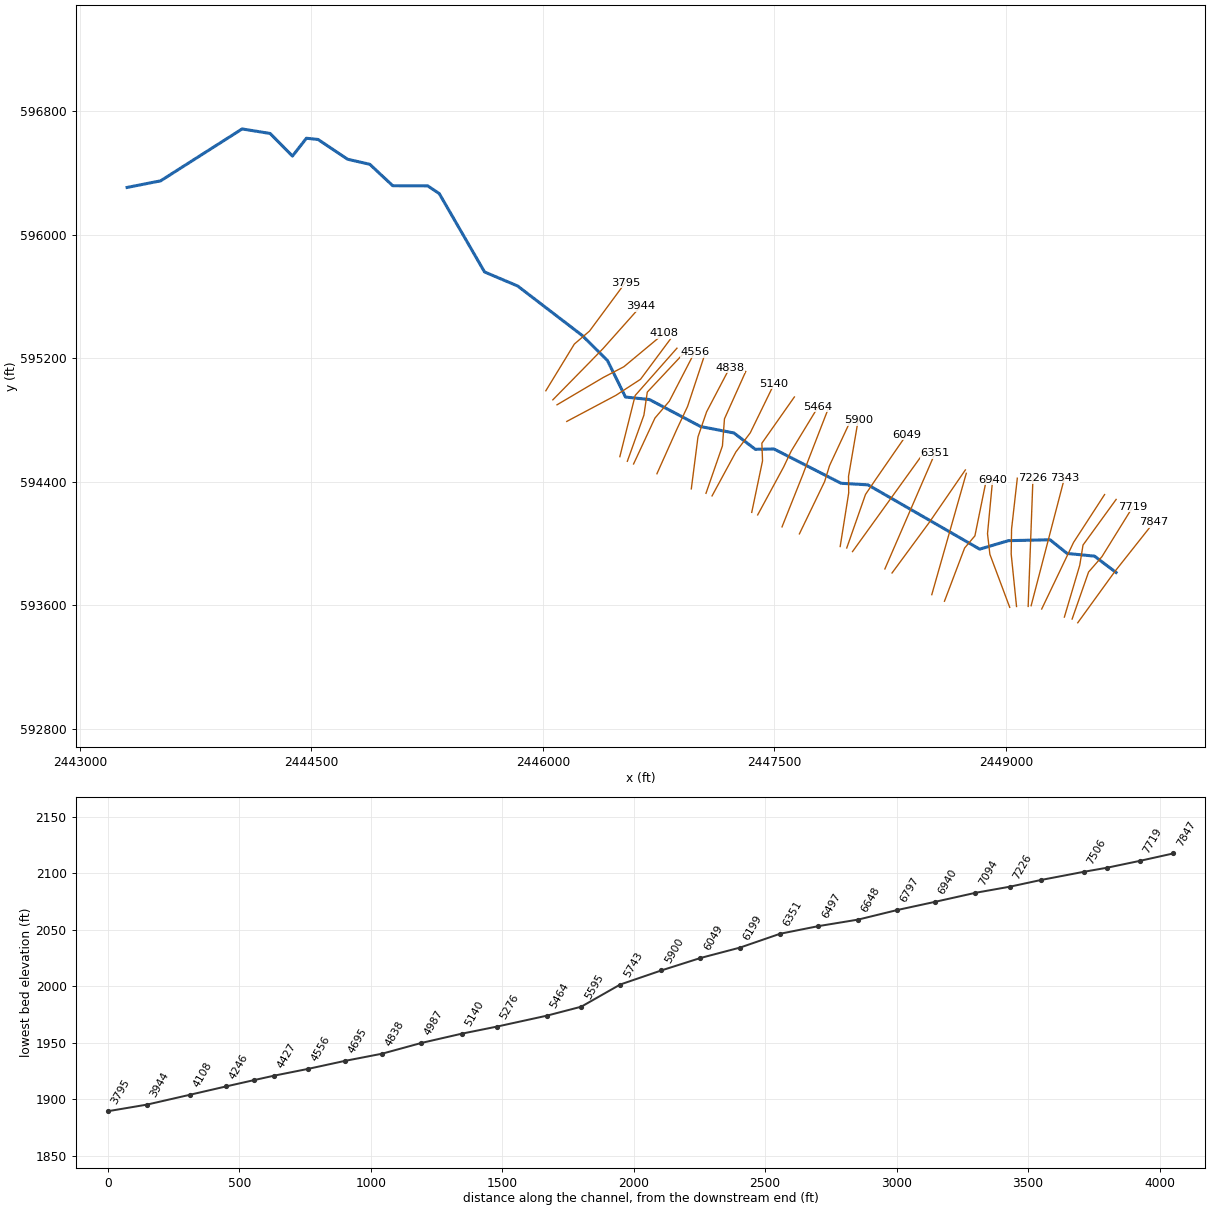
--- PROPSTRN.prj (project) ---

Proj Title=PROPSTRN
Current Plan=p01
Default Exp/Contr=0,0
English Units
Geom File=g01
Flow File=f01
Plan File=p01
Background Map Layer=Inundation Boundary (P10yr Value_0)
Background Map Layer=Inundation Boundary (P100yr Value_0)
Background Map Layer=Inundation Boundary (P500yr Value_0)
BEGIN DESCRIPTION:
Stream Name: Propst Run
Flood Zone: Approximate
Pendlteon County, West Virginia
HEC-RAS Version: 5.0.7
Hydrology Method:
Regression
END DESCRIPTION:
DSS Export Rating Curves= 0
DSS Export Rating Curve Sorted= 0
DSS Export Volume Flow Curves= 0
DXF OffsetX= 0
DXF OffsetY= 0
DXF ScaleX= 0
DXF ScaleY= 0

--- PROPSTRN.p01 (plan) ---

Plan Title=Floodplain
Program Version=5.07
Short Identifier=Floodplain
Geom File=g01
Flow File=f01
Subcritical Flow
K Sum by GR= 0
Std Step Tol= 0.01
Critical Tol= 0.01
Num of Std Step Trials= 20
Max Error Tol= 0.3
Flow Tol Ratio= 0.001
Split Flow NTrial= 30
Split Flow Tol= 0.02
Split Flow Ratio= 0.02
Log Output Level= 0
Friction Slope Method= 1
Unsteady Friction Slope Method= 2
Unsteady Bridges Friction Slope Method= 1
Parabolic Critical Depth
Global Vel Dist= 0 , 0 , 0
Global Log Level= 0
CheckData=True
Encroach Param=-1 ,0,0, 0
Mapping Interval=1HOUR
Computation Time Step Use Courant=        0
Computation Time Step Use Time Series=    0
Computation Time Step Count To Double=0
Computation Time Step Max Doubling=0
Computation Time Step Max Halving=0
Computation Time Step Residence Courant=0
Run HTab= 0
Run UNet= 0
Run Sediment= 0
Run PostProcess= 0
Run WQNet= 0
Run RASMapper=-1
UNET Theta= 0
UNET Theta Warmup= 0
UNET ZTol= 0
UNET ZSATol= 0
UNET MxIter= 0
UNET Max Iter WO Improvement= 0
UNET MaxInSteps= 0
UNET DtIC= 0
UNET DtMin= 0
UNET MaxCRTS= 0
UNET WFStab= 0
UNET SFStab= 0
UNET WFX= 1
UNET SFX= 1
UNET 1D Methodology=Finite Difference
UNET DSS MLevel= 1
UNET Pardiso=0
UNET DZMax Abort= 0
UNET Use Existing IB Tables= 0
UNET Froude Reduction=False
UNET Froude Limit= 0
UNET Froude Power= 0
UNET D1 Cores= 0
UNET D2 Coriolis=0
UNET D2 Cores= 0
UNET D2 Theta= 1
UNET D2 Theta Warmup= 1
UNET D2 Z Tol= 0.01
UNET D2 Volume Tol= 0.01
UNET D2 Max Iterations= 20
UNET D2 Equation= 0
UNET D2 RampUpFraction=0.1
UNET D2 TimeSlices= 1
UNET D2 BCVolumeCheck=0
UNET D1D2 MaxIter= 0
UNET D1D2 ZTol=0.01
UNET D1D2 QTol=0.1
UNET D1D2 MinQTol=1
Write IC File= 0
Write IC File at Fixed DateTime=0
Write IC File at Sim End=0
Echo Input=False
Echo Parameters=False
Echo Output=False
Write Detailed= 0
HDF Write Warmup=0
HDF Write Time Slices=0
HDF Flush=0
HDF Face Node Velocities=0
HDF Compression= 1
HDF Chunk Size= 1
HDF Spatial Parts= 1
HDF Use Max Rows=0
HDF Fixed Rows= 1
Calibration Method= 0
Calibration Iterations= 20
Calibration Max Change=0.05
Calibration Tolerance=0.2
Calibration Maximum=1.5
Calibration Minimum=0.5
Calibration Optimization Method= 1
WQ AD Non Conservative
WQ ULTIMATE=-1
WQ Max Comp Step=1HOUR
WQ Output Interval=15MIN
WQ Output Selected Increments= 0
WQ Output face flow=0
WQ Output face velocity=0
WQ Output face area=0
WQ Output face dispersion=0
WQ Output cell volume=0
WQ Output cell surface area=0
WQ Output cell continuity=0
WQ Output cumulative cell continuity=0
WQ Output face conc=0
WQ Output face dconc_dx=0
WQ Output face courant=0
WQ Output face peclet=0
WQ Output face adv mass=0
WQ Output face disp mass=0
WQ Output cell mass=0
WQ Output cell source sink temp=0
WQ Output nsm pathways=0
WQ Output nsm derived pathways=0
WQ Output MaxMinRange=-1
WQ Daily Max Min Mean=-1
WQ Daily Range=0
WQ Daily Time=0
WQ Create Restart=0
WQ Fixed Restart=0
WQ System Summary=0
WQ Write To DSS=0
WQ Use Fixed Temperature=0
Sorting and Armoring Iterations= 10
XS Update Threshold= 0.02
Bed Roughness Predictor= 0
Hydraulics Update Threshold= 0.02
Energy Slope Method= 1
Volume Change Method= 1
Sediment Retention Method= 0
XS Weighting Method= 0
Number of US Weighted Cross Sections= 1
Number of DS Weighted Cross Sections= 1
Upstream XS Weight=0
Main XS Weight=1
Downstream XS Weight=0
Number of DS XS's Weighted with US Boundary= 1
Upstream Boundary Weight= 1
Weight of XSs Associated with US Boundary= 0
Number of US XS's Weighted with DS Boundary= 1
Downstream Boundary Weight= 0.5
Weight of XSs Associated with DS Boundary= 0.5
Percentile Method= 0
Sediment Output Level= 3
Mass or Volume Output= 0
Output Increment Type= 1
Profile and TS Output Increment= 1
XS Output Flag= 0
XS Output Increment= 10
Write Gradation File= 0
Read Gradation Hotstart= 0
Write HDF5 File= 1
Write Binary Output= 1
Write DSS Sediment File= 0
SV Curve= 0
Specific Gage Flag= 0

--- PROPSTRN.f01 (steady flow) ---

Flow Title=Flows
Program Version=5.07
Number of Profiles= 6
Profile Names=P100yr,P10yr,P25yr,P50yr,P500yr,P101yr
River Rch & RM=PROPSTRN,Main            ,7847
     437     205     289     361     638     531
River Rch & RM=PROPSTRN,Main            ,7343
     758     353     500     625    1114     922
River Rch & RM=PROPSTRN,Main            ,5743
     853     397     562     703    1255    1038
Boundary for River Rch & Prof#=PROPSTRN,Main            , 1
Up Type= 0
Dn Type= 3
Dn Slope=0.045744
Boundary for River Rch & Prof#=PROPSTRN,Main            , 2
Up Type= 0
Dn Type= 3
Dn Slope=0.045744
Boundary for River Rch & Prof#=PROPSTRN,Main            , 3
Up Type= 0
Dn Type= 3
Dn Slope=0.045744
Boundary for River Rch & Prof#=PROPSTRN,Main            , 4
Up Type= 0
Dn Type= 3
Dn Slope=0.045744
Boundary for River Rch & Prof#=PROPSTRN,Main            , 5
Up Type= 0
Dn Type= 3
Dn Slope=0.045744
Boundary for River Rch & Prof#=PROPSTRN,Main            , 6
Up Type= 0
Dn Type= 3
Dn Slope=0.045744
DSS Import GetInterval= 0
DSS Import GetPeak= 0
DSS Import FillOption= 0

--- PROPSTRN.g01 (geometry) ---

Geom Title=Geometry
Program Version=5.07

River Reach=PROPSTRN        ,Main
Reach XY= 30
     2449714.236      593812.937     2449574.475      593918.746
     2449397.122      593936.221     2449286.476      594024.845
     2449016.317      594018.989     2448830.576      593964.112
     2448106.818      594380.694     2447931.968       594391.03
     2447497.877      594613.023     2447376.889      594610.911
     2447237.963      594716.929     2447022.869       594758.29
     2446690.644      594933.547     2446535.531      594949.641
     2446418.993      595185.798     2446254.912      595348.805
     2445837.298      595668.913     2445622.346      595760.201
     2445328.673      596268.386     2445254.301      596318.017
     2445027.265      596318.961     2444879.051      596457.701
     2444735.304      596490.366      2444543.23       596618.64
     2444468.259      596626.472     2444377.873      596511.107
     2444232.748      596657.481     2444051.608      596686.738
     2443523.441      596350.325     2443306.647       596307.73

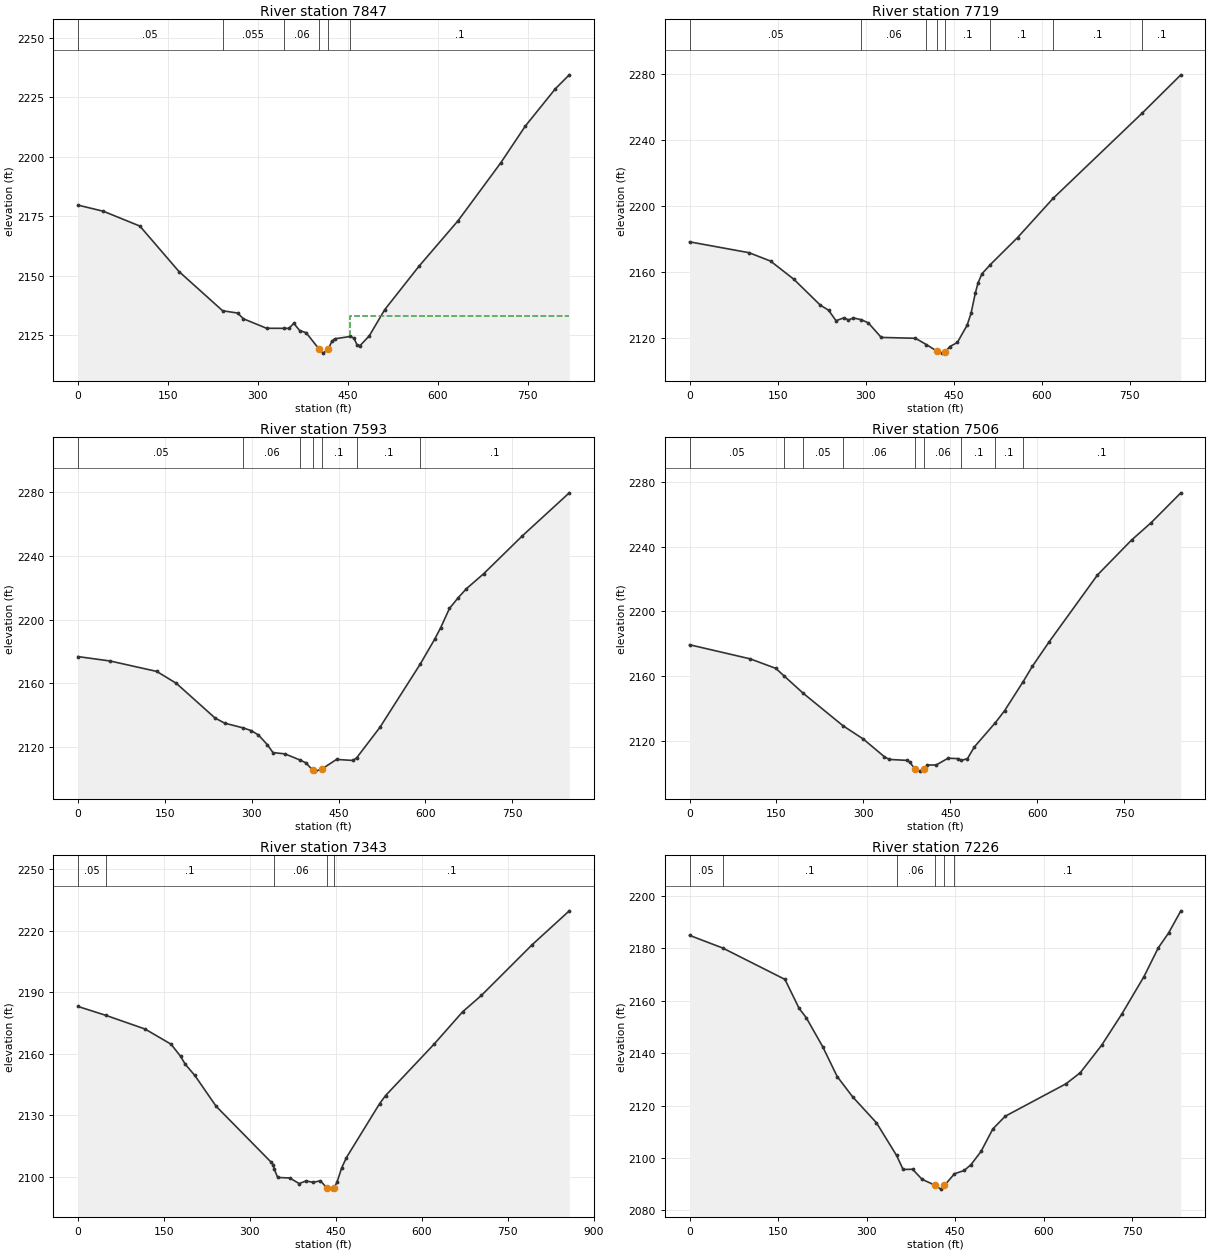
Type RM Length L Ch R = 1 ,7847    ,128.3,128.3,128.3
XS GIS Cut Line= 3
     2449465.979      593487.079     2449706.395      593819.144
     2449960.515      594140.153
#Sta/Elev= 30
       0  2179.7    42.4 2177.11   103.2  2170.9   168.4 2151.82  241.25 2135.34
   266.2 2134.38     276 2131.96   314.5 2127.99  343.882127.958   351.7 2127.94
     360 2130.05   369.9 2126.98   380.4 2126.16   402.5 2119.14     409 2117.55
   417.52119.282   423.3 2122.44     428 2123.56  454.432124.555   460.3 2123.82
   465.4 2121.05   470.5 2120.72   485.9 2124.84   511.5 2135.77   568.5 2153.97
     634 2173.17   705.1 2197.45     746 2212.86   796.3 2228.58   819.4  2234.4
#Mann= 6 ,-1 , 0
       0     .05       0  241.25    .055       0  343.88     .06       0
   402.5    .045       0   417.5     .06       0  454.43      .1       0
#XS Ineff= 2 , 0
                          453.96         2133.31
Permanent Ineff=
       F       F
Bank Sta=402.5,417.5
XS Rating Curve= 0 ,0
Exp/Cntr=0.3,0.1

Type RM Length L Ch R = 1 ,7719    ,118.8,125.6,132.2
XS GIS Cut Line= 4
     2449429.492      593511.0192449536.07056231593815.717836363
 2449622.8006942593915.416456011     2449824.138      594240.396
#Sta/Elev= 30
       0 2178.29   101.3 2171.71     138 2166.64   177.6 2155.67   222.7    2140
   236.9 2136.91   249.6 2130.55   263.5 2132.32   270.8    2131   279.3 2132.22
     293 2131.11   304.7  2129.2   326.7 2120.42     385 2119.91  403.412116.123
   420.92112.284   430.9 2110.92   435.62111.565   443.3 2114.83   456.3 2117.36
   472.9 2127.75   479.7 2135.06     487 2147.32   491.7 2153.55   498.2 2158.91
  512.612164.523     559 2180.89  619.422204.558  771.382256.221   837.2 2279.37
#Mann= 8 ,-1 , 0
       0     .05       0     293     .06       0  403.41      .1       0
   420.9    .045       0   435.6      .1       0  512.61      .1       0
  619.42      .1       0  771.38      .1       0
Bank Sta=420.9,435.6
XS Rating Curve= 0 ,0
Exp/Cntr=0.3,0.1

Type RM Length L Ch R = 1 ,7593    ,90.3,86.9,83.4
XS GIS Cut Line= 4
     2449379.346      593523.8892449479.03313521593859.953850578
2449500.07451635593990.4157869212449714.75795008594286.349153058
#Sta/Elev= 30
       0  2176.8    55.6 2174.02     136 2167.48   169.8    2160   236.5 2138.25
   253.2 2134.97  285.692131.933   299.1 2130.28   311.6 2127.54     327 2121.42
   336.7 2116.46   357.3 2115.66   383.82111.725   393.8 2109.97   405.12105.434
     410 2104.81   420.62106.021   446.4 2112.16   474.8 2111.52  481.332113.245
   521.2 2132.25  590.752171.973   615.7 2187.61   626.3 2194.98   641.4 2207.06
   656.7 2213.89   670.7 2219.47   700.4 2228.85   767.4 2252.73   848.3 2279.73
#Mann= 7 ,-1 , 0
       0     .05       0  285.69     .06       0   383.8      .1       0
   405.1    .045       0   420.6      .1       0  481.33      .1       0
  590.75      .1       0
Bank Sta=405.1,420.6
XS Rating Curve= 0 ,0
Exp/Cntr=0.3,0.1

Type RM Length L Ch R = 1 ,7506    ,160.8,163.6,164.2
XS GIS Cut Line= 3
2449232.46326742 593576.214936672449438.71142743  594007.4610894
2449639.84599668594317.685594526
#Sta/Elev= 30
       0 2179.42   104.7 2170.69     149 2164.79  163.342160.065  196.082149.437
  265.182129.231   299.8 2121.12   336.4 2110.11   344.6 2108.51   375.1 2107.92
   379.6 2106.96   389.32102.433   397.3 2101.27     4042102.314   410.6 2105.03
   425.6 2105.08   446.1 2109.24   463.8    2109  468.862107.945   479.5 2108.96
   491.3 2116.17  527.562131.157   543.8 2138.73  575.282156.378   591.4    2166
     620 2180.96   703.9 2222.56   762.7 2244.15   796.4 2254.85   847.8 2273.36
#Mann= 9 ,-1 , 0
       0     .05       0  163.34      .1       0  196.08     .05       0
  265.18     .06       0   389.3    .045       0     404     .06       0
  468.86      .1       0  527.56      .1       0  575.28      .1       0
Bank Sta=389.3,404
XS Rating Curve= 0 ,0
Exp/Cntr(USF)=0,0
Exp/Cntr=0.3,0.1

Type RM Length L Ch R = 1 ,7343    ,113.9,116.9,118.4
XS GIS Cut Line= 2
2449163.93610678593597.4811814882449380.35821719594426.937861158
#Sta/Elev= 30
       0 2183.07   48.652178.737     117 2172.07   162.4 2164.67     179 2158.75
   187.2 2154.87   203.8 2149.45     241 2134.41   336.8  2107.2   340.2 2105.96
  342.742103.622   348.4 2099.68   369.5 2099.42   385.9  2096.7     398 2097.98
   410.5 2097.29   422.9 2098.08   434.5 2094.53   443.5 2093.99   446.7 2094.59
   451.8 2097.29   460.1 2104.33   468.3 2109.34   526.2 2135.65   536.7 2139.63
   621.3 2164.69   671.1 2180.48     704 2188.49   792.4 2213.17   857.2 2229.71
#Mann= 5 ,-1 , 0
       0     .05       0   48.65      .1       0  342.74     .06       0
   434.5    .045       0   446.7      .1       0
Bank Sta=434.5,446.7
XS Rating Curve= 0 ,0
Exp/Cntr=0.3,0.1

Type RM Length L Ch R = 1 ,7226    ,130.7,131.5,131.6
XS GIS Cut Line= 2
     2449144.729      593593.133     2449175.872      594424.885
#Sta/Elev= 30
       0 2184.94   56.022180.127   161.6 2168.14   185.7 2157.05   197.7 2153.53
   225.7 2142.41   250.1 2131.07   276.3 2123.33   316.7 2113.41  350.62    2101
   361.8  2095.6   377.8  2095.7   393.8 2091.87   416.32089.542   425.8 2088.11
   431.82089.511  448.812093.976   465.3 2095.22   476.9 2097.48   493.8  2102.5
   513.8 2111.09   534.8 2115.93   637.9 2128.33   661.8 2132.51     698 2142.98
   732.5 2154.99   769.9 2169.24     794 2180.16   811.5 2185.84   832.3  2194.3
#Mann= 6 ,-1 , 0
       0     .05       0   56.02      .1       0  350.62     .06       0
   416.3    .045       0   431.8     .06       0  448.81      .1       0
Bank Sta=416.3,431.8
XS Rating Curve= 0 ,0
Exp/Cntr=0.3,0.1

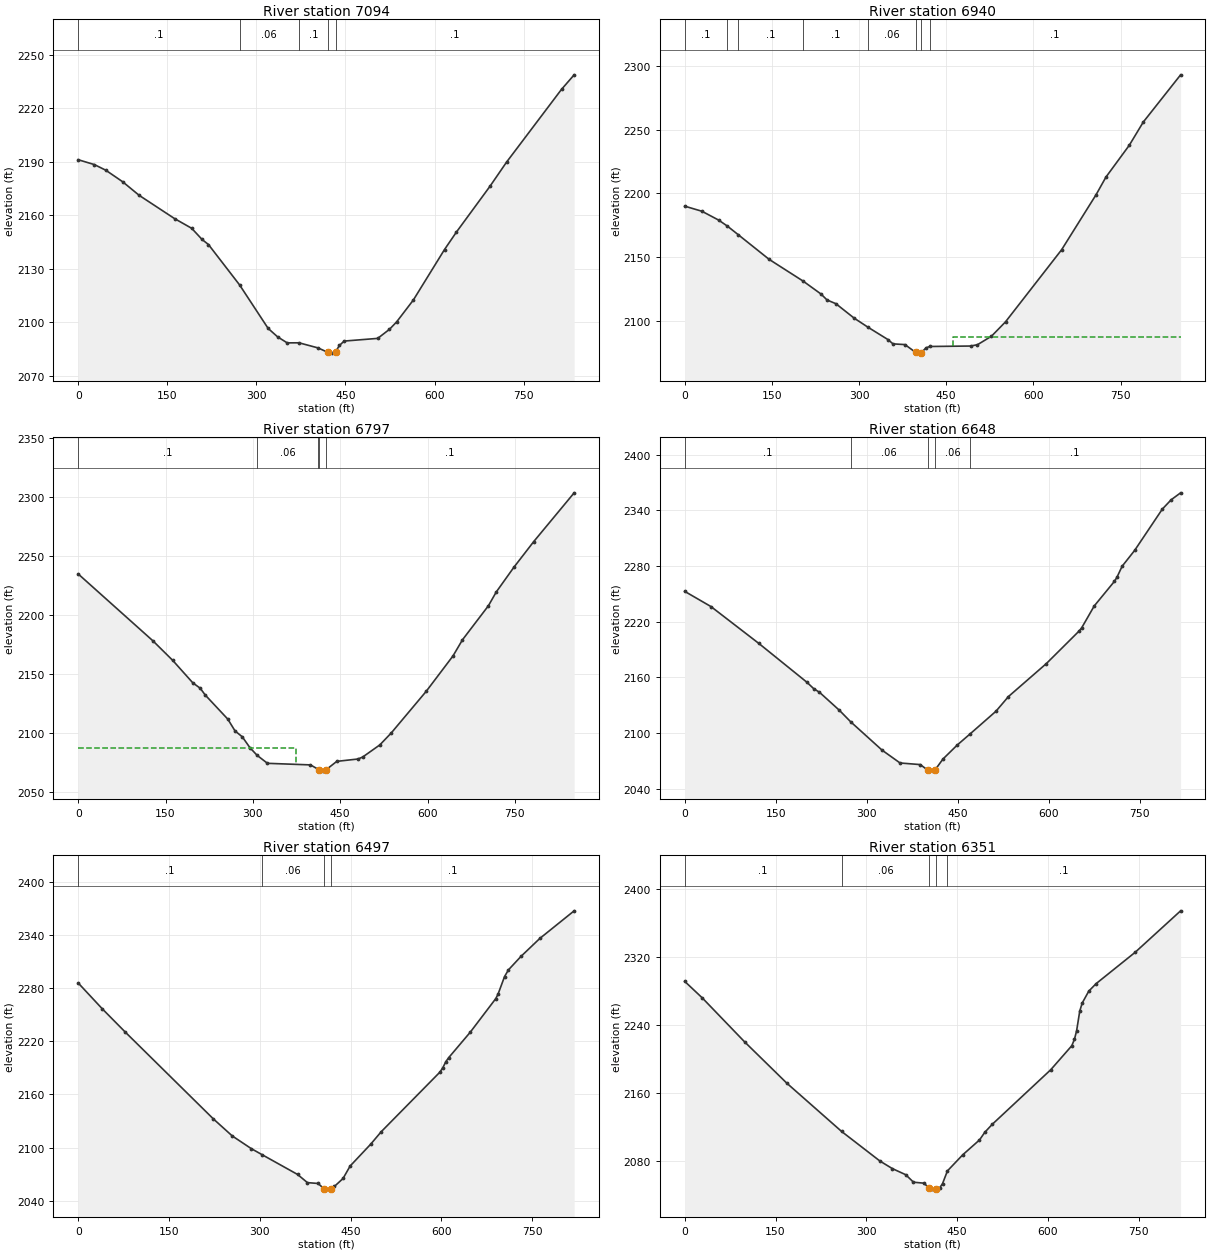
Type RM Length L Ch R = 1 ,7094    ,152,154.1,155.9
XS GIS Cut Line= 4
     2449069.374       593592.532449034.73775866 593932.46175849
2449037.16046975 594094.06033091     2449074.405      594423.751
#Sta/Elev= 30
       0 2191.05    27.2 2188.33    46.4 2185.18    74.7 2178.74   102.7 2171.08
   162.2 2158.07   191.1 2152.62   208.6 2146.35   219.3 2143.53  271.692120.914
   319.8 2096.53   335.8 2091.78   351.9 2088.42  371.792088.454   403.9 2085.59
   419.9 2083.17   427.9 2082.67   433.4 2083.44   439.9    2087   447.9 2089.43
   504.3 2090.93     524 2095.98   536.1 2100.14   564.3 2112.42   616.8 2140.72
   636.7 2150.44   693.1 2176.05   721.2 2189.67   813.8 2230.48   835.1 2238.63
#Mann= 5 ,-1 , 0
       0      .1       0  271.69     .06       0  371.79      .1       0
   419.9    .045       0   433.4      .1       0
Bank Sta=419.9,433.4
XS Rating Curve= 0 ,0
Exp/Cntr=0.3,0.1

Type RM Length L Ch R = 1 ,6940    ,153.3,143.7,137.4
XS GIS Cut Line= 4
     2449025.243      593586.9422448896.67080858593930.757228242
2448881.31769752594064.098633389     2448914.547      594414.553
#Sta/Elev= 30
       0 2189.97    29.6 2185.98    58.5 2179.02   73.612174.266   91.882167.668
   145.5 2148.16  203.752131.176   234.6 2121.01     245 2116.33   260.2 2113.43
   291.6  2102.1  315.632094.903   349.9 2085.24   358.4 2081.92     379 2081.34
   397.62075.173   403.2 2074.65   407.2 2075.13   415.3 2078.79  421.712079.858
   491.8 2080.22   503.7 2081.23   527.9 2087.94     552 2099.19   648.5 2155.73
   707.9 2198.99   724.8 2212.77     765 2237.76   789.1 2255.99   853.3 2293.01
#Mann= 8 ,-1 , 0
       0      .1       0   73.61      .1       0   91.88      .1       0
  203.75      .1       0  315.63     .06       0   397.6    .045       0
   407.2     .06       0  421.71      .1       0
#XS Ineff= 2 , 0
                          461.22         2087.39
Permanent Ineff=
       F       F
Bank Sta=397.6,407.2
XS Rating Curve= 0 ,0
Exp/Cntr=0.3,0.1

Type RM Length L Ch R = 1 ,6797    ,143.5,148.8,152.8
XS GIS Cut Line= 4
2448602.41372595593626.6445160332448733.03590478593971.665954193
2448799.63807471594050.246195703     2448875.521        594422.6
#Sta/Elev= 30
       0 2234.88   128.3  2178.1   162.5  2161.4   196.8 2142.43   209.6  2137.8
   218.1 2132.11     257 2111.56   269.4 2101.53   281.8 2096.59   295.1 2087.24
  307.442080.771   325.1 2074.04     399  2072.7  412.732068.828   413.92068.493
     420 2067.41   425.6 2068.52   444.2 2075.71   480.5  2077.7   488.6 2079.37
   518.1 2089.68   537.6 2099.76     598 2135.33   643.8 2165.27   660.1 2178.99
   704.6 2207.87   718.1 2219.59   748.6 2240.73   782.5 2262.41   851.9 2303.81
#Mann= 5 ,-1 , 0
       0      .1       0  307.44     .06       0  412.73      .1       0
   413.9    .045       0   425.6      .1       0
#XS Ineff= 2 , 0
          374.48 2086.76
Permanent Ineff=
       F       F
Bank Sta=413.9,425.6
XS Rating Curve= 0 ,0
Exp/Cntr=0.3,0.1

Type RM Length L Ch R = 1 ,6648    ,154.9,150.5,147.4
XS GIS Cut Line= 2
     2448520.179      593669.0322448743.83537831      594455.517
#Sta/Elev= 30
       0 2252.78    43.3 2236.38   122.4 2196.55   201.3 2154.88     213 2147.69
   222.1 2144.04   255.1 2124.51  273.63 2112.16   325.5 2081.53   355.1 2067.71
   388.4 2065.98   400.72060.065   409.2 2058.93   412.7 2060.11   425.8 2071.93
   449.3 2087.01  470.17 2098.81   513.2 2123.47   533.9 2139.37   596.3 2174.87
   650.4 2210.03   654.5 2213.36   675.3 2237.04   708.6 2263.57   712.7 2267.91
   721.3 2279.87   741.9  2296.9   787.6  2341.5   802.2 2351.55   817.7 2358.99
#Mann= 5 ,-1 , 0
       0      .1       0  273.63     .06       0   400.7    .045       0
   412.7     .06       0  470.17      .1       0
Bank Sta=400.7,412.7
XS Rating Curve= 0 ,0
Exp/Cntr=0.3,0.1

Type RM Length L Ch R = 1 ,6497    ,144.2,146.3,148.5
XS GIS Cut Line= 3
     2448262.734      593809.698     2448505.485      594139.388
     2448737.772       594477.28
#Sta/Elev= 30
       0 2285.77      40 2256.46    77.2 2230.75   223.1 2132.56   254.5 2113.21
     286 2098.88  304.052091.963   362.6 2069.69   378.7 2060.53   396.3 2059.56
   406.2 2053.63   408.5 2053.18   416.9  2053.8   423.4 2056.26   437.6 2065.18
   449.3 2079.23   483.2 2103.81   500.7 2117.95   597.8 2185.28   602.6 2190.33
   607.5 2197.02   612.3 2201.61   647.8 2230.22     690 2268.17   693.8 2273.27
   704.5 2293.03     711 2300.62   731.6 2315.74   762.8 2336.05   819.5 2367.19
#Mann= 4 ,-1 , 0
       0      .1       0  304.05     .06       0   406.2    .045       0
   416.9      .1       0
Bank Sta=406.2,416.9
XS Rating Curve= 0 ,0
Exp/Cntr=0.3,0.1

Type RM Length L Ch R = 1 ,6351    ,153.7,151.7,148.7
XS GIS Cut Line= 2
     2448216.361      593835.862     2448542.026      594587.387
#Sta/Elev= 30
       0 2291.02    29.2 2271.42    98.9 2219.83   168.7 2171.13  259.242114.263
   322.5 2079.45     343 2070.56   365.1 2063.35   377.9 2054.54   395.3 2053.39
   404.1 2047.27   408.4 2046.39   415.9 2047.01   421.5 2048.21   425.9 2052.89
  433.952067.832   459.3 2086.83   486.9 2104.26   495.8 2113.39     508 2122.69
   604.6 2186.94   639.4 2215.24   643.8 2222.92   647.3 2232.73   652.5 2255.96
   656.5 2265.37   667.4 2279.48   679.6 2288.35   744.1 2325.25   819.1 2374.03
#Mann= 5 ,-1 , 0
       0      .1       0  259.24     .06       0   404.1    .045       0
   415.9     .06       0  433.95      .1       0
Bank Sta=404.1,415.9
XS Rating Curve= 0 ,0
Exp/Cntr=0.3,0.1

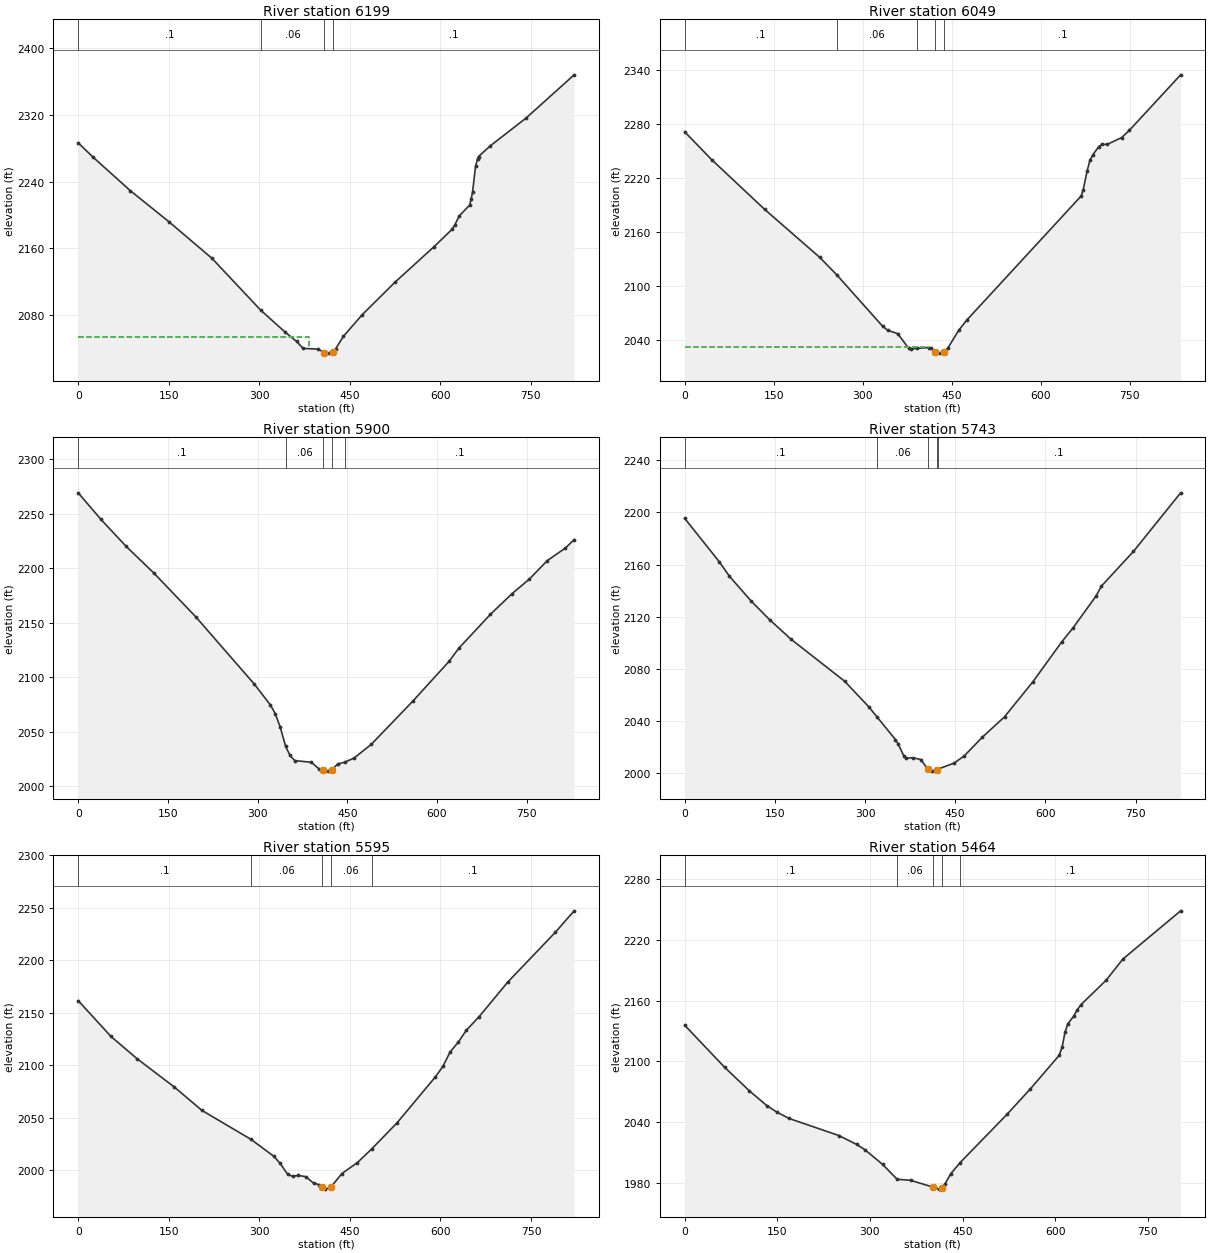
Type RM Length L Ch R = 1 ,6199    ,150.4,150.7,151
XS GIS Cut Line= 2
     2448006.724      593948.341     2448487.251      594615.117
#Sta/Elev= 30
       0  2286.5    23.9 2269.77    86.6 2228.95     150 2192.04   221.6 2147.97
  302.262085.876     343 2059.33     362 2048.15   372.6 2039.89   397.2    2039
   407.8 2034.87   416.4 2034.19   422.1 2035.09   426.8 2039.45   439.3 2054.19
   470.8 2080.38   525.1 2119.37   589.5 2161.76   619.8  2182.9     624  2187.8
   631.3 2198.65   648.7 2211.85   651.4  2219.6   653.6 2227.82   658.5 2258.54
   661.9 2267.42   663.4 2270.08   683.2 2283.02   742.3 2316.27   821.9 2368.09
#Mann= 4 ,-1 , 0
       0      .1       0  302.26     .06       0   407.8    .045       0
   422.1      .1       0
#XS Ineff= 2 , 0
          383.22 2053.27
Permanent Ineff=
       F       F
Bank Sta=407.8,422.1
XS Rating Curve= 0 ,0
Exp/Cntr=0.3,0.1

Type RM Length L Ch R = 1 ,6049    ,141.3,149,156.4
XS GIS Cut Line= 4
     2447969.292      593971.5872448090.81730109594318.578374413
 2448155.7115098 594414.16200656     2448356.146      594704.377
#Sta/Elev= 30
       0 2271.14    45.6  2240.1   134.6 2184.97   227.8 2131.38  256.482111.944
   333.8 2054.73   342.3 2050.38   359.2 2046.55   377.4 2030.39   382.2 2029.25
  390.94 2030.26   411.2 2031.17     416  2030.2   422.52026.611   430.5 2024.96
   437.22026.309   444.1 2031.17   461.9  2050.4   476.3  2062.3   668.4 2199.83
   671.8 2206.77   678.1    2227     683 2239.34   687.9  2245.5   697.9 2254.66
   703.5 2257.19   712.2 2257.16   736.5 2264.73   749.5 2272.79   835.9 2334.52
#Mann= 5 ,-1 , 0
       0      .1       0  256.48     .06       0  390.94      .1       0
   422.5    .045       0   437.2      .1       0
#XS Ineff= 2 , 0
          409.97 2031.68
Permanent Ineff=
       F       F
Bank Sta=422.5,437.2
XS Rating Curve= 0 ,0
Exp/Cntr=0.3,0.1

Type RM Length L Ch R = 1 ,5900    ,159.8,156.2,152.3
XS GIS Cut Line= 4
     2447926.739      593980.9992447981.98015445594328.966756628
2447980.82670636594435.639087684     2448043.434      594800.757
#Sta/Elev= 30
       0 2269.22    38.1 2244.78    80.1 2220.14   126.4 2195.69   196.3 2155.66
   294.2 2093.97   321.6 2074.53   329.7 2066.48   337.8 2054.43  346.972036.654
   354.1 2028.46     362  2023.6     390 2022.02     402  2016.3   409.42014.997
     418 2013.92   424.22015.186     434 2020.44  445.772022.137   461.5 2025.94
   490.1 2038.45   559.3 2077.91   620.3 2114.61   636.5 2126.59   689.2 2157.62
   725.9 2176.86   754.2 2189.87   784.5 2206.99     815 2218.65   829.5 2226.27
#Mann= 5 ,-1 , 0
       0      .1       0  346.97     .06       0   409.4    .045       0
   424.2     .06       0  445.77      .1       0
Bank Sta=409.4,424.2
XS Rating Curve= 0 ,0
Exp/Cntr=0.3,0.1

Type RM Length L Ch R = 1 ,5743    ,148.8,148.3,147.2
XS GIS Cut Line= 4
     2447662.427      594062.8692447825.82230499594401.733378314
2447858.10052851594506.206639949     2448001.824      594813.632
#Sta/Elev= 30
       0 2195.41    57.5 2162.15    74.2 2151.15   110.7  2131.9   141.8 2117.42
   177.3 2102.52     266 2070.49   306.1 2050.88   320.52042.738   350.5 2025.72
     355 2022.44   364.8 2012.85   368.3 2011.42   380.1 2011.69   392.9 2010.35
   404.42002.925   410.6 2001.47   419.82002.695  420.912002.945   448.3 2007.67
     465 2013.15   494.6 2027.28     532 2043.16   578.9 2069.87   627.2 2100.65
   645.4 2111.05   684.2  2135.8   693.2 2143.45   746.4 2170.02   824.9 2215.01
#Mann= 5 ,-1 , 0
       0      .1       0   320.5     .06       0   404.4    .045       0
   419.8     .06       0  420.91      .1       0
Bank Sta=404.4,419.8
XS Rating Curve= 0 ,0
Exp/Cntr=0.3,0.1

Type RM Length L Ch R = 1 ,5595    ,132,131.2,129.9
XS GIS Cut Line= 4
     2447549.849      594108.2752447684.61107332594446.486837752
2447721.56765565594544.558570527     2447849.046      594873.239
#Sta/Elev= 30
       0 2161.47    54.2 2127.38    97.2 2106.25   158.8 2079.31   204.9 2056.87
  286.272029.219   324.1 2013.09   334.3 2006.44     347 1995.82     355 1994.08
   364.2 1994.84     377 1993.71   389.8 1987.52   398.4 1986.15   403.21983.681
   408.5 1981.82   418.21983.593   436.8  1996.7   462.5 2007.15  485.912020.011
   528.1 2045.02   591.2 2088.54     604  2098.8   615.9 2112.53   629.8 2122.09
   642.6 2133.14   664.1  2146.3   711.7 2179.35   790.3 2226.66   821.4  2247.1
#Mann= 5 ,-1 , 0
       0      .1       0  286.27     .06       0   403.2    .045       0
   418.2     .06       0  485.91      .1       0
Bank Sta=403.2,418.2
XS Rating Curve= 0 ,0
Exp/Cntr=0.3,0.1

Type RM Length L Ch R = 1 ,5464    ,183.5,188.3,193.8
XS GIS Cut Line= 4
     2447392.144      594185.8632447560.25453666 594496.24306552
2447609.58001836594599.7853505612447783.93522777594886.453382215
#Sta/Elev= 30
       0 2135.71    64.5  2094.3   104.3 2071.17   132.8 2056.44   149.3  2049.9
   169.2 2043.61   249.6 2026.81   278.3 2018.08     292 2012.75   320.5 1998.29
  344.081983.616   365.9 1982.55     4021975.895   412.4 1973.86   416.91975.395
     422 1979.41   430.9 1989.04  446.022000.003   522.3 2047.87   559.9 2072.87
   606.7 2106.11   611.4 2114.37     616 2128.91   620.7 2137.33     630 2144.51
   635.8 2150.94   641.6 2155.87   682.4 2180.04   709.7 2201.06   803.2 2248.68
#Mann= 5 ,-1 , 0
       0      .1       0  344.08     .06       0     402    .045       0
   416.9     .06       0  446.02      .1       0
Bank Sta=402,416.9
XS Rating Curve= 0 ,0
Exp/Cntr=0.3,0.1

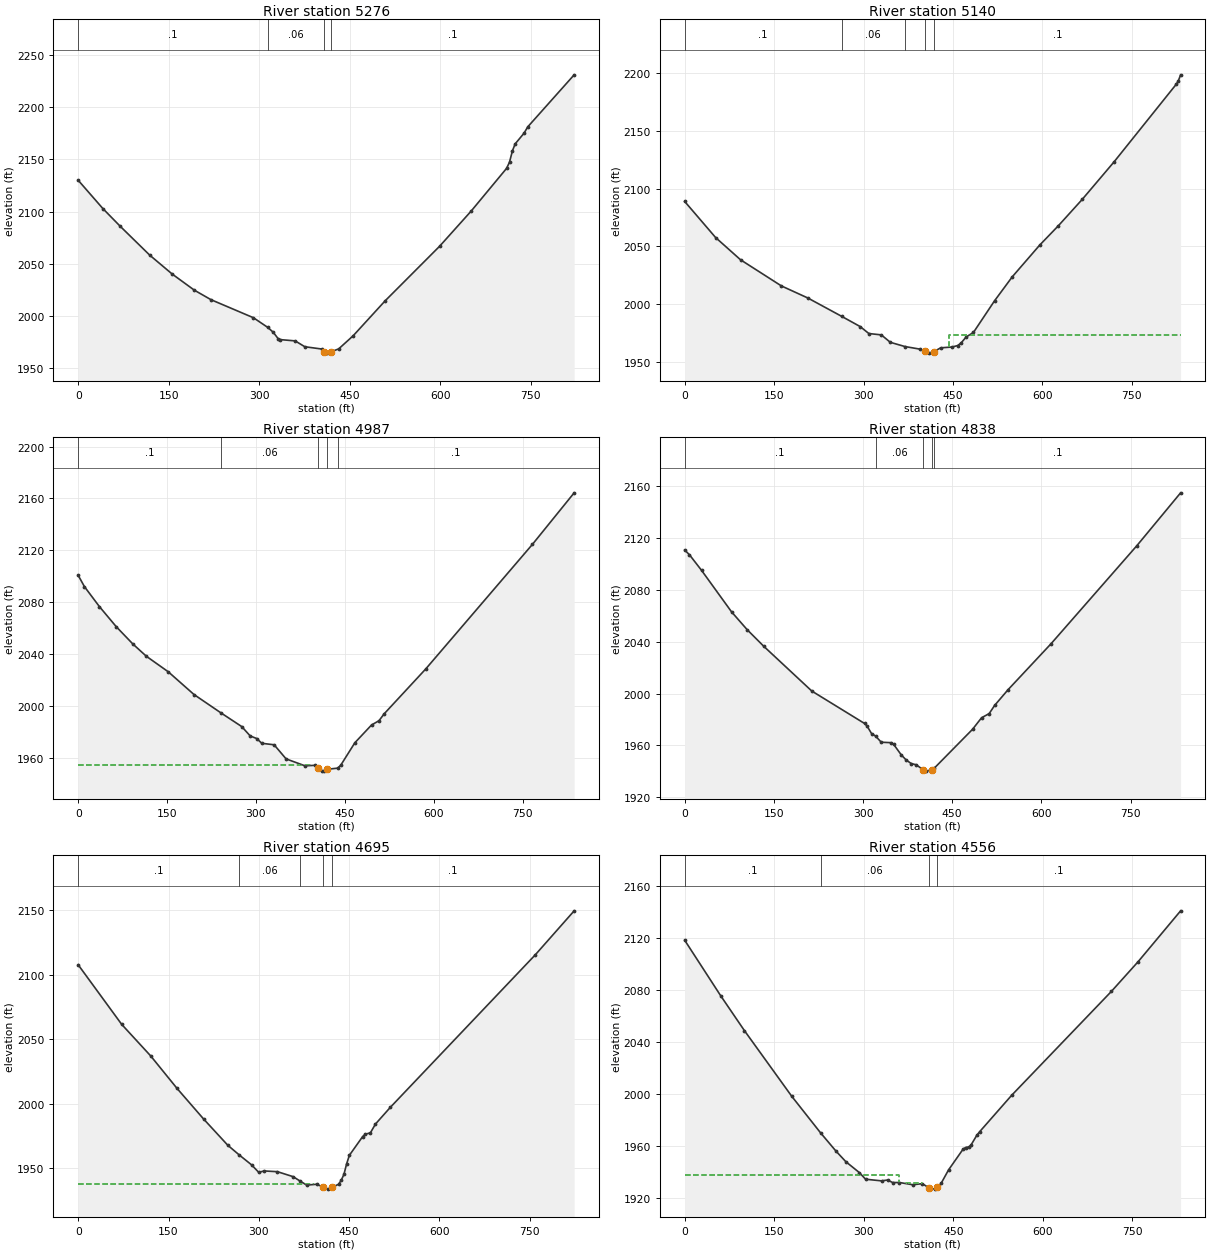
Type RM Length L Ch R = 1 ,5276    ,142.4,135.6,127.2
XS GIS Cut Line= 4
     2447353.629      594202.3412447423.65007332594536.218216066
2447419.35444269594650.4098989252447629.94563339594950.196524958
#Sta/Elev= 30
       0 2130.02    40.9 2102.87    69.7 2085.85   118.6 2058.18   155.8 2040.07
   192.3 2024.68     220 2015.52   290.4 1998.19  314.181988.887   323.1 1984.32
   331.3 1978.12   334.8 1977.22   359.5    1976   375.5 1970.39   403.5  1968.2
   407.5 1965.66   411.5 1964.26     4191965.542   431.6 1968.32   455.6  1980.9
   508.4  2014.3   598.9 2066.79   651.1 2100.46   709.8 2141.43   714.7 2147.44
   719.5 2158.25   724.1 2164.98   738.7 2175.15     745 2181.33   821.8 2231.16
#Mann= 4 ,-1 , 0
       0      .1       0  314.18     .06       0   407.5    .045       0
     419      .1       0
Bank Sta=407.5,419
XS Rating Curve= 0 ,0
Exp/Cntr=0.3,0.1

Type RM Length L Ch R = 1 ,5140    ,145.9,153.3,160.2
XS GIS Cut Line= 4
     2447096.476       594309.012447250.90006552594593.760679405
2447344.18465875594717.909296743      2447498.72       595035.04
#Sta/Elev= 30
       0 2088.85    51.9 2057.69    93.7  2038.5   162.3 2015.91   206.6  2005.5
  263.121989.734   294.3 1980.86     309 1974.82   329.9 1973.65     345 1967.23
  369.571963.582     395 1961.32     403 1959.55     410  1957.9   418.21959.252
   429.4 1962.46   448.7 1963.19     458 1964.44   463.7 1966.68   472.3 1971.88
   484.4 1975.73   519.8 2003.04   549.7 2023.88   595.6 2051.17   626.8 2067.81
   666.8 2090.54   720.3    2123     825 2190.24   827.9 2192.63     832 2198.17
#Mann= 5 ,-1 , 0
       0      .1       0  263.12     .06       0  369.57      .1       0
     403    .045       0   418.2      .1       0
#XS Ineff= 2 , 0
                          443.57         1973.24
Permanent Ineff=
       F       F
Bank Sta=403,418.2
XS Rating Curve= 0 ,0
Exp/Cntr=0.3,0.1

Type RM Length L Ch R = 1 ,4987    ,152.1,149,145.7
XS GIS Cut Line= 4
     2447057.234       594325.852447163.77215055594633.064675504
2447176.97024143594808.4198529092447314.71908893595114.994382215
#Sta/Elev= 30
       0 2100.64    10.5 2091.99    35.7 2076.62    64.3 2061.03    92.2 2047.76
   115.1 2038.25     152  2026.3   195.5 2008.75  241.081994.575     276 1984.06
   290.3 1976.83   301.4 1974.82   309.8 1971.17   330.7 1970.01   350.9 1959.13
   382.8 1953.79   398.9 1954.16   405.31952.054   410.9 1949.75   414.3  1949.7
   420.3 1951.14  437.841951.984     443 1954.16     467 1971.61   495.1 1985.28
   507.7 1988.59   516.5 1993.94   586.7 2028.55   766.7 2124.58   837.1 2164.31
#Mann= 5 ,-1 , 0
       0      .1       0  241.08     .06       0   405.3    .045       0
   420.3     .06       0  437.84      .1       0
#XS Ineff= 2 , 0
          394.76  1954.6
Permanent Ineff=
       F       F
Bank Sta=405.3,420.3
XS Rating Curve= 0 ,0
Exp/Cntr=0.3,0.1

Type RM Length L Ch R = 1 ,4838    ,144,142.9,141.3
XS GIS Cut Line= 4
     2446962.111      594354.5562447005.28960148594691.309202962
2447060.99400336594853.368315547     2447211.145      595139.704
#Sta/Elev= 30
       0 2110.85     8.1 2107.14    28.3  2095.2    78.9 2063.09   104.9 2049.47
   133.1 2036.51   213.8 2002.02   302.5    1977   306.5 1975.21   314.3 1969.23
  321.07 1967.24   330.7 1962.51   347.2 1962.17   351.4 1960.93   364.1 1952.86
   372.6 1948.79     381 1946.07   389.5  1945.1   401.41941.172   406.4 1940.21
   416.21941.391  419.871942.519   484.2 1972.49   499.4  1981.4   512.2 1984.61
   521.3 1990.89   543.8 2002.97   616.1 2038.43   760.6 2114.18   834.2 2154.97
#Mann= 5 ,-1 , 0
       0      .1       0  321.07     .06       0   401.4    .045       0
   416.2     .06       0  419.87      .1       0
Bank Sta=401.4,416.2
XS Rating Curve= 0 ,0
Exp/Cntr=0.3,0.1

Type RM Length L Ch R = 1 ,4695    ,142.1,139.1,135.7
XS GIS Cut Line= 4
     2446739.398      594452.6592446869.26624547594742.802490948
2446938.11441778594889.265722569     2447046.247      595215.843
#Sta/Elev= 30
       0 2107.69    72.2 2061.53   120.4 2037.05   164.2 2011.84   208.1 1988.23
   248.5 1967.76  267.671960.187   287.9  1952.6   299.8 1946.82   308.8 1947.87
   330.9 1947.29     357 1943.43  369.051939.855   379.5 1936.89   396.3 1937.55
   405.81935.474   414.4 1933.77   420.91935.034   432.4 1937.53   436.9 1940.67
   441.4  1945.3   445.8 1953.38   450.4 1960.01   472.3 1974.43   476.7 1976.33
   485.3 1977.43   493.7 1984.23   518.5 1997.25   759.1 2115.43   823.7 2149.57
#Mann= 5 ,-1 , 0
       0      .1       0  267.67     .06       0  369.05      .1       0
   405.8    .045       0   420.9      .1       0
#XS Ineff= 2 , 0
           392.1 1937.83
Permanent Ineff=
       F       F
Bank Sta=405.8,420.9
XS Rating Curve= 0 ,0
Exp/Cntr=0.3,0.1

Type RM Length L Ch R = 1 ,4556    ,122,128.9,135.4
XS GIS Cut Line= 4
     2446587.999      594515.8822446726.41022847594813.223516456
2446819.37684071594922.401790589     2446984.406       595241.55
#Sta/Elev= 30
       0 2118.04    60.3 2075.37     100 2048.61   179.4 1998.05  227.941969.814
   253.3 1956.03   269.9 1947.85   292.5 1939.48     303 1934.36   329.7 1933.09
   339.9 1933.73   348.4 1931.79   359.8 1931.83   382.2 1930.09     398 1930.96
   408.81927.831     419 1926.74   423.31927.995   429.5 1931.13     442 1941.52
   466.3 1957.45   470.4 1958.68     476 1959.17   479.3 1960.41   489.5 1968.24
     494 1970.81   547.5 1998.76   714.7 2078.67   759.7 2101.63   830.7 2140.62
#Mann= 4 ,-1 , 0
       0      .1       0  227.94     .06       0   408.8    .045       0
   423.3      .1       0
#XS Ineff= 2 ,-1
       0  358.69 1937.26   370.6  397.24 1931.13
Permanent Ineff=
       F       F
Bank Sta=408.8,423.3
XS Rating Curve= 0 ,0
Exp/Cntr=0.3,0.1

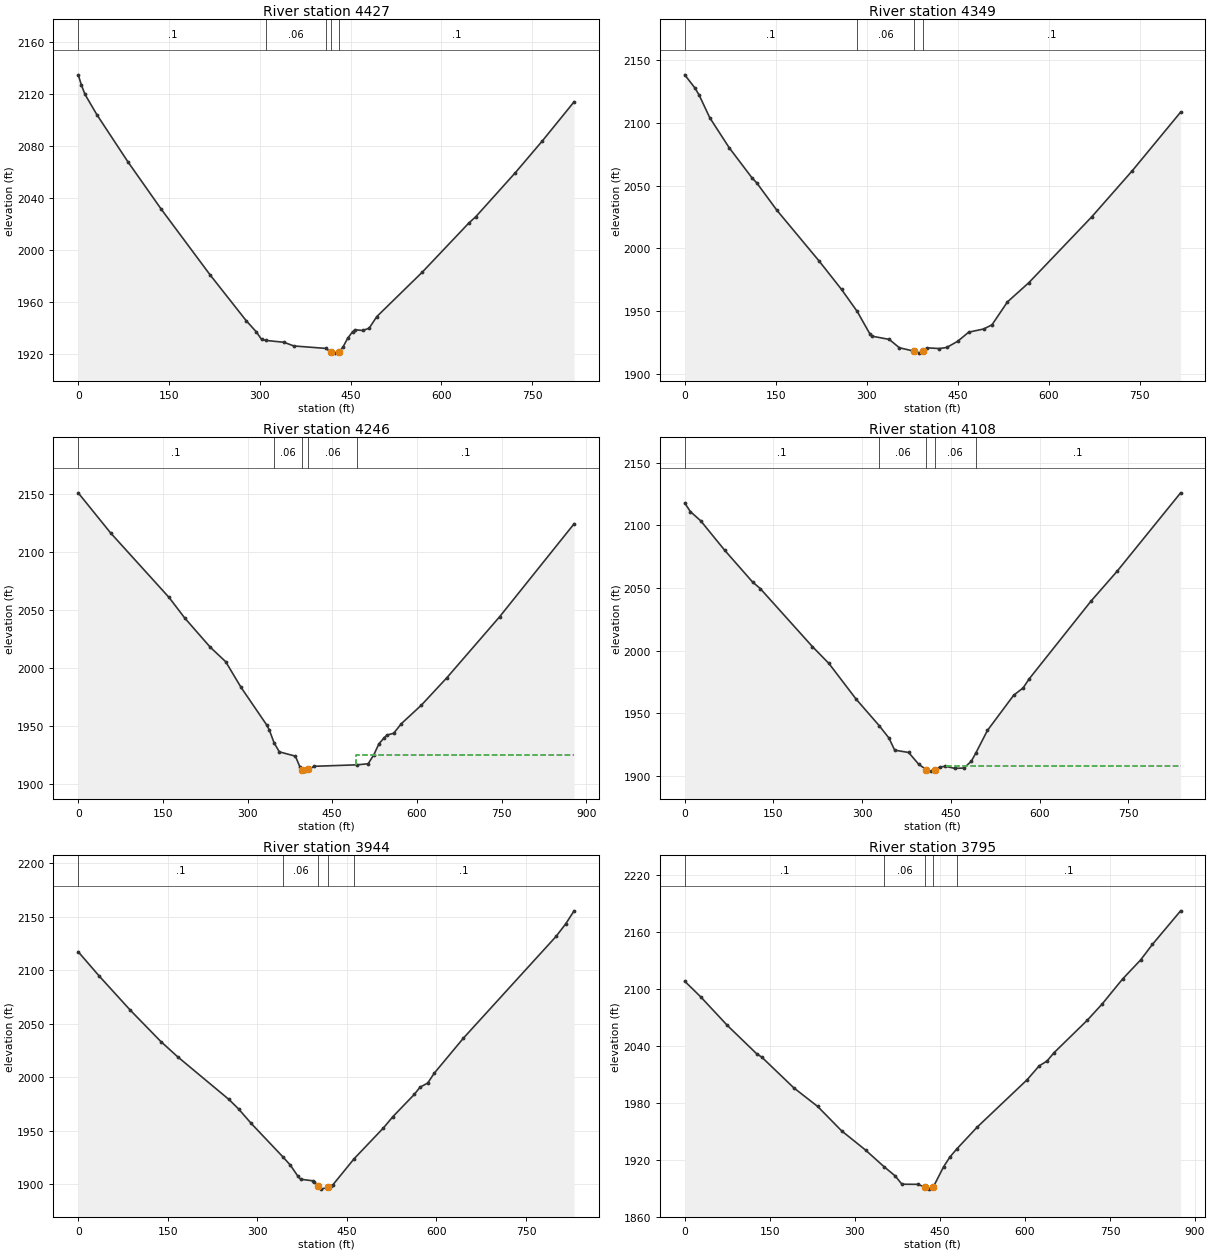
Type RM Length L Ch R = 1 ,4427    ,79.1,77.9,76.6
XS GIS Cut Line= 4
     2446547.677      594533.4872446655.07717011594832.658273035
2446676.91840702594981.7007545262446916.93681404595237.377516456
#Sta/Elev= 30
       0 2134.92     5.4 2126.92    11.3 2119.81    30.8 2104.27    81.9 2068.13
   137.1 2031.56   217.9 1980.96   277.4  1945.8   294.4 1937.03   302.8 1931.31
  310.921930.497     340 1929.09   356.2 1926.27  408.581924.401   417.31921.779
   424.9 1920.75   430.81921.753     437  1925.1   445.1 1932.13   453.2 1937.17
   457.2 1938.75     470 1938.17   480.6 1939.93   493.3 1948.88   568.4 1983.06
   645.2 2020.81     657 2025.83     722 2059.54   766.9 2084.15   819.2 2114.16
#Mann= 5 ,-1 , 0
       0      .1       0  310.92     .06       0  408.58      .1       0
   417.3    .045       0   430.8      .1       0
Bank Sta=417.3,430.8
XS Rating Curve= 0 ,0
Exp/Cntr=0.3,0.1

Type RM Length L Ch R = 1 ,4349    ,110.5,103.3,94.2
XS GIS Cut Line= 3
2446499.06151652594563.4277203722446598.46972058594959.679867111
2446869.08094274595266.188496297
#Sta/Elev= 30
       0 2138.22    16.9 2127.69    23.9 2121.96    41.2 2104.13    73.3  2080.2
   110.5 2056.47   118.7 2052.23   151.7 2030.56   221.8 1989.86   258.4 1967.45
  284.361949.862   304.9 1932.27   308.2 1930.28   337.2 1927.64   353.7 1921.02
   378.21918.265   386.7 1916.73   392.2 1918.48   399.1 1920.96   419.8 1920.38
   431.9 1921.24     450 1926.19   468.1 1933.42   492.8 1935.94   506.5 1939.31
     532 1957.53   567.1 1972.74   670.9  2025.2   737.8 2061.93   817.4 2108.53
#Mann= 4 ,-1 , 0
       0      .1       0  284.36     .06       0   378.2    .045       0
   392.2      .1       0
Bank Sta=378.2,392.2
XS Rating Curve= 0 ,0
Exp/Cntr(USF)=0,0
Exp/Cntr=0.3,0.1

Type RM Length L Ch R = 1 ,4246    ,138,137.4,136.2
XS GIS Cut Line= 4
     2446155.192      594791.6372446473.30526248594960.563957487
 2446632.9864581595064.6107491752446828.53570351595327.705330499
#Sta/Elev= 30
       0 2150.62    57.4 2116.13     161 2060.62   188.8 2042.94   234.1 2017.81
   261.3  2005.4   288.4 1983.42   333.7 1951.19   338.3 1947.03   347.21935.476
   356.4 1927.88   384.8 1924.18   393.1 1914.58   396.7 1912.31   396.7  1912.3
   402.5  1911.3   407.61912.732   418.2 1915.46  494.531916.736   513.7 1917.64
   523.9 1925.48   532.8 1934.81   542.3 1940.06   547.1  1942.3     559  1943.9
   572.8 1952.24     608 1968.04   652.9 1991.47   746.8 2044.14   878.6 2123.99
#Mann= 5 ,-1 , 0
       0      .1       0   347.2     .06       0   396.7    .045       0
   407.6     .06       0  494.53      .1       0
#XS Ineff= 2 , 0
                          492.77         1925.48
Permanent Ineff=
       F       F
Bank Sta=396.7,407.6
XS Rating Curve= 0 ,0
Exp/Cntr=0.3,0.1

Type RM Length L Ch R = 1 ,4108    ,160,164,167.8
XS GIS Cut Line= 4
     2446092.164      594899.3372446389.60088097595075.198245474
2446525.29423704595146.070249724     2446786.686       595363.34
#Sta/Elev= 30
       0 2117.93     9.5 2111.09      27 2103.72    67.9 2080.02   114.6 2054.93
   127.6 2049.68   215.8 2003.35   243.7 1989.91   289.8 1961.38  328.721940.273
   345.3 1930.32     355 1920.67   378.6  1918.8   395.9 1909.25   408.31905.205
   416.4 1903.92     423 1904.89   431.7 1907.21   440.7 1907.79   456.4 1906.14
   472.3 1906.39   484.6 1911.87  491.871918.041   511.8 1936.37   556.2 1964.48
   572.3  1970.4   581.8 1977.19   686.8 2039.54   730.8 2063.28   838.5 2126.05
#Mann= 5 ,-1 , 0
       0      .1       0  328.72     .06       0   408.3    .045       0
     423     .06       0  491.87      .1       0
#XS Ineff= 2 , 0
                          441.05         1907.85
Permanent Ineff=
       F       F
Bank Sta=408.3,423
XS Rating Curve= 0 ,0
Exp/Cntr=0.3,0.1

Type RM Length L Ch R = 1 ,3944    ,150.5,149.7,147.9
XS GIS Cut Line= 4
     2446065.094      594931.7352446306.09923697595177.260575973
2446389.98862595595263.427157295     2446633.583       595536.97
#Sta/Elev= 30
       0 2117.38    35.5 2094.44    86.9 2062.88   138.4 2033.35   166.4 2019.14
   252.5 1979.09   268.5 1970.31   289.7 1956.71  342.591925.507   355.3 1917.67
   368.1 1907.14   372.5 1904.43   392.9 1902.95   395.7 1902.06   401.6 1897.87
   407.2 1895.16   418.3    1897   423.9 1897.91   426.8 1899.35  462.251923.682
   511.3 1952.49   527.3 1963.15   562.8 1983.76   572.5 1990.55   585.4 1994.49
   596.5 2003.78   645.1 2036.42   800.5 2131.81   816.5 2143.46   830.6 2155.69
#Mann= 5 ,-1 , 0
       0      .1       0  342.59     .06       0   401.6    .045       0
   418.3     .06       0  462.25      .1       0
Bank Sta=401.6,418.3
XS Rating Curve= 0 ,0
Exp/Cntr=0.3,0.1

Type RM Length L Ch R = 1 ,3795    ,141.9,142,142
XS GIS Cut Line= 4
2446019.58649818594990.3813808262446204.23244132595292.892153058
2446302.83599438595377.3238684632446534.80487901595691.188907438
#Sta/Elev= 30
       0 2108.06      28 2091.73    75.1 2061.58   126.7 2031.82   136.1 2028.06
   192.3 1995.88   234.5 1976.24   276.6 1950.64   318.8 1930.41  351.941912.648
     371 1903.24     383 1894.44   410.7 1894.32   422.91891.687   430.4 1889.27
     4381891.161   456.7    1913   467.4 1922.88  479.861931.627   515.5  1954.4
   603.9 2004.46   624.9 2018.91   638.9 2024.09     651 2032.69   709.5 2066.79
   736.1 2084.08   772.1 2110.38     804  2130.5   824.7  2146.8   874.5 2182.16
#Mann= 5 ,-1 , 0
       0      .1       0  351.94     .06       0   422.9    .045       0
     438     .06       0  479.86      .1       0
Bank Sta=422.9,438
XS Rating Curve= 0 ,0
Exp/Cntr=0.3,0.1