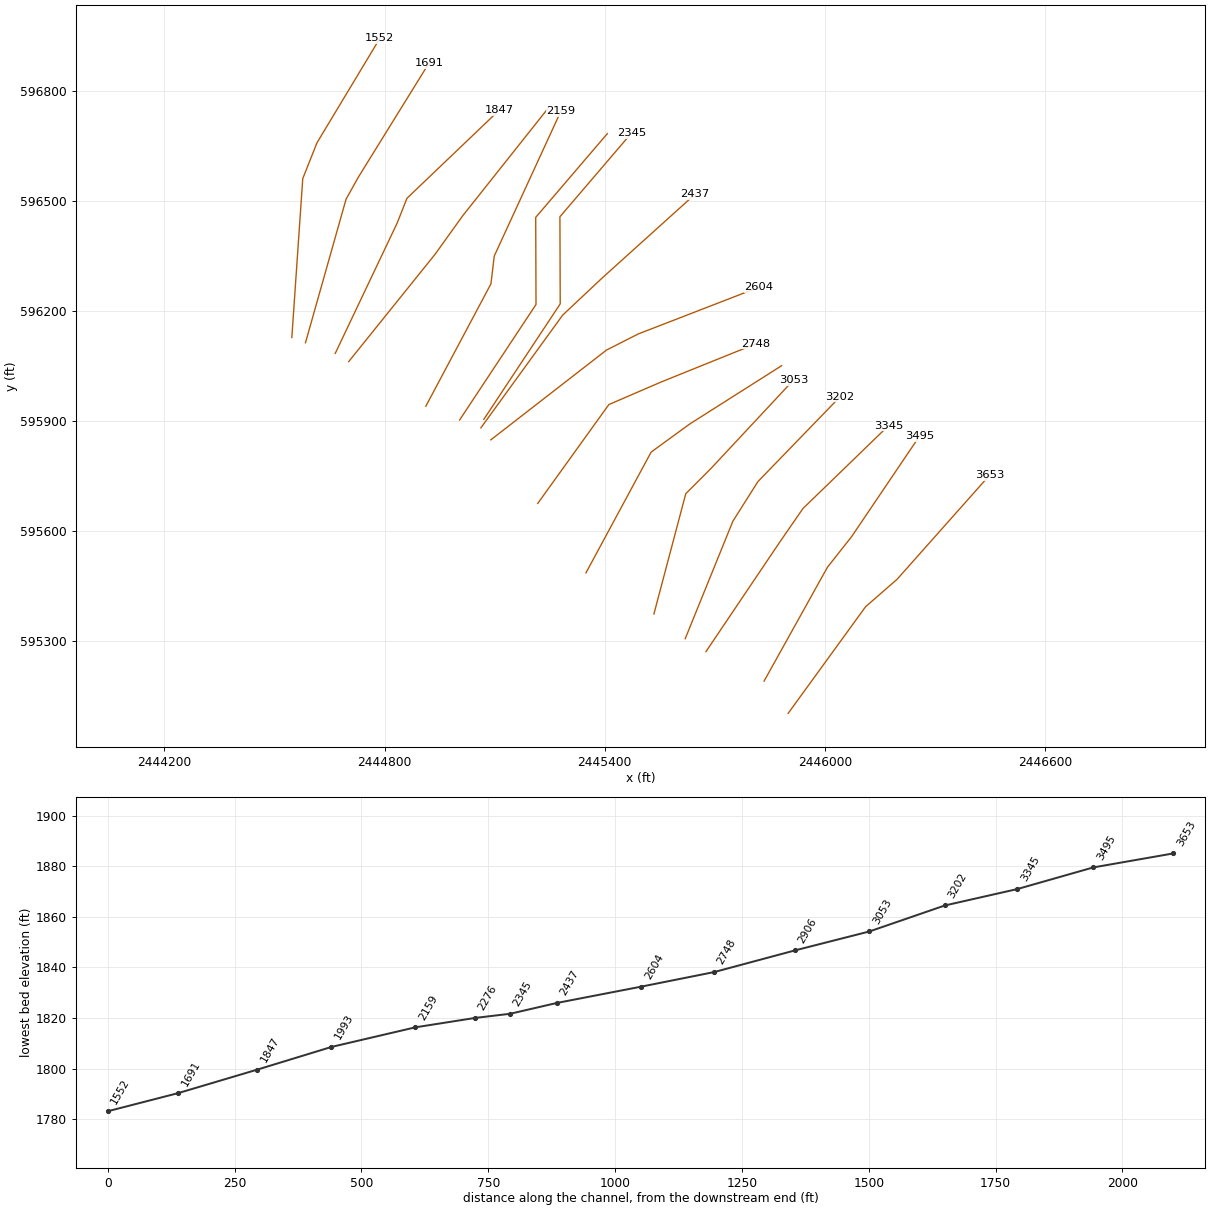
HEC-RAS study PROPSTRN.prj: PROPSTRN

--- PROPSTRN.g01 (geometry) --- (continued)

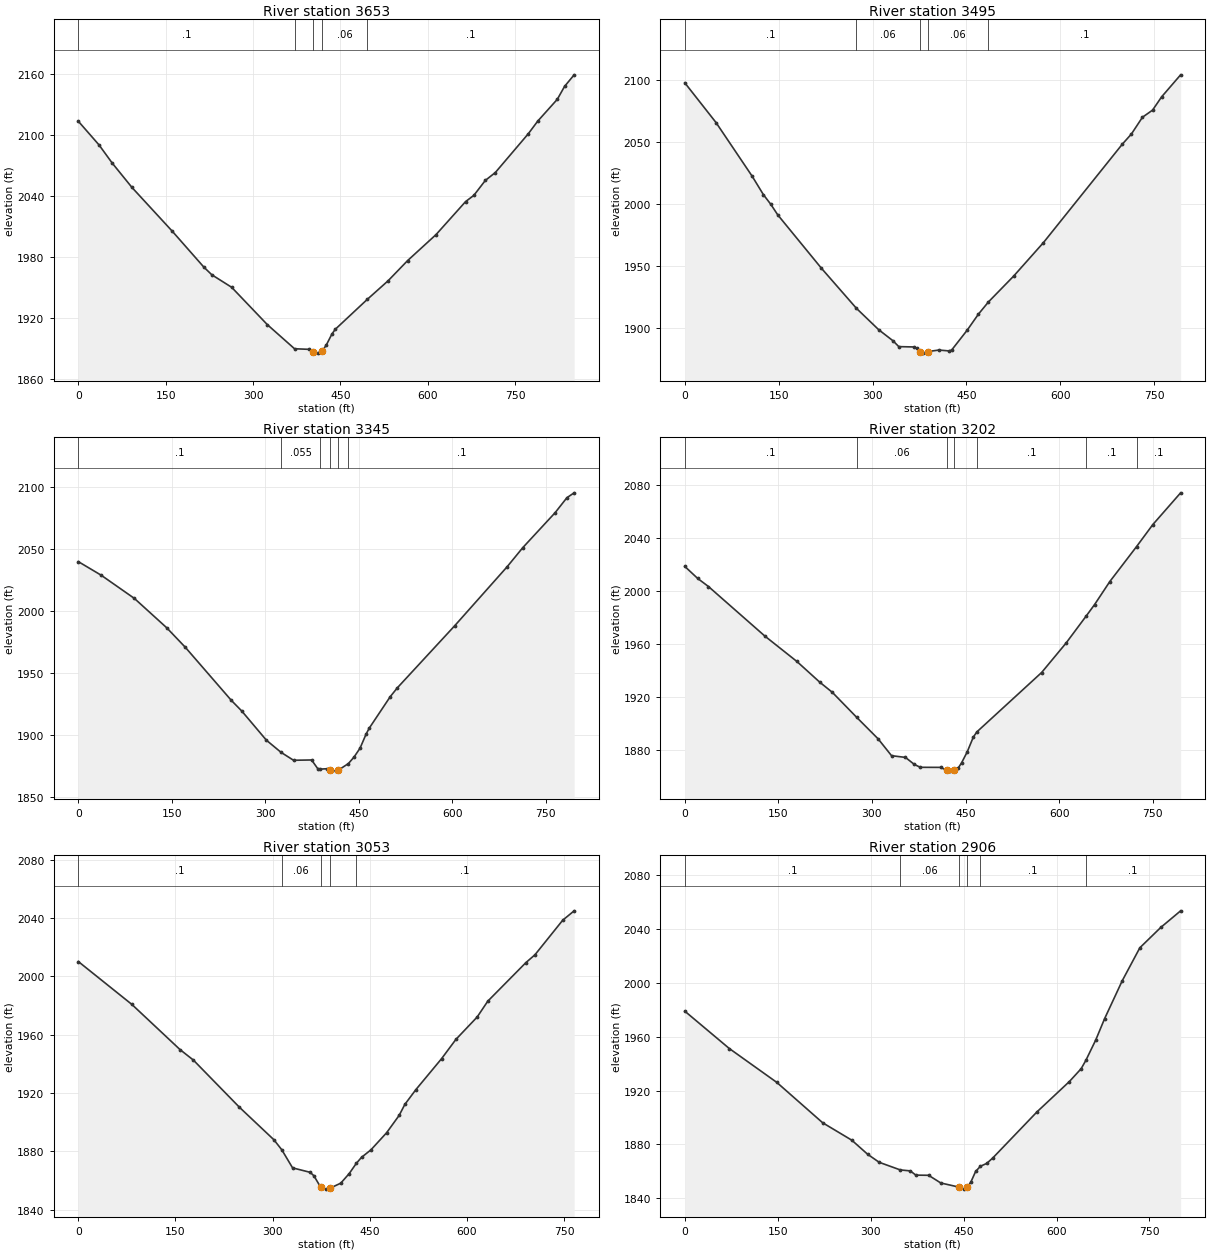
Type RM Length L Ch R = 1 ,3653    ,155.7,158.1,160.5
XS GIS Cut Line= 4
      2445899.35      595103.9742446110.22407636595394.369170942
2446196.04690744595469.1726654552446447.45749818595752.034879008
#Sta/Elev= 30
       0 2113.62    35.6 2090.24    58.1 2072.44    92.1 2048.35   161.1 2005.32
   215.5 1969.82   229.1  1962.3   263.2 1949.94   324.4 1913.15  371.181889.339
   395.6 1888.78     4031886.626   411.6 1885.03   418.41886.657     426 1893.35
   435.3 1903.79     441 1908.47  496.341938.169   531.7  1956.3   565.4 1976.32
   614.1 2001.89   664.8 2034.41     679 2040.57   698.8 2055.35   715.8 2063.03
   772.5 2101.32   788.7 2113.78   822.3 2135.29   834.8 2148.05   851.2  2159.4
#Mann= 5 ,-1 , 0
       0      .1       0  371.18     .06       0     403    .045       0
   418.4     .06       0  496.34      .1       0
Bank Sta=403,418.4
XS Rating Curve= 0 ,0
Exp/Cntr=0.3,0.1

Type RM Length L Ch R = 1 ,3495    ,148.9,149.8,150.2
XS GIS Cut Line= 4
2445833.75330248595191.7424234712446006.24773123595501.754576562
2446072.53384694595585.792149422     2446257.554      595859.581
#Sta/Elev= 30
       0 2098.06    49.9 2065.93   107.5 2022.64   125.7 2007.55   137.5 1999.76
   148.6 1991.21   218.3 1948.11  274.221915.716   309.8 1898.42   332.7 1889.45
   341.9 1884.75   365.9 1884.48     371 1883.24   376.1 1880.77   381.2 1879.49
   388.51880.761     406 1881.98   421.9 1881.29   426.3 1881.94   451.2 1898.06
   469.1 1910.98  485.121920.865   525.4 1941.76   572.8 1968.72   699.1 2048.48
   713.6 2056.69   731.2 2070.22   747.4 2075.99   761.9 2086.75   792.2 2104.52
#Mann= 5 ,-1 , 0
       0      .1       0  274.22     .06       0   376.1    .045       0
   388.5     .06       0  485.12      .1       0
Bank Sta=376.1,388.5
XS Rating Curve= 0 ,0
Exp/Cntr=0.3,0.1

Type RM Length L Ch R = 1 ,3345    ,142.5,142.8,143.3
XS GIS Cut Line= 4
     2445675.519      595272.1242445875.88692529595569.562743801
2445939.77105157595661.980419869 2446172.9621957595887.831790082
#Sta/Elev= 30
       0 2039.53    36.6 2028.63      90 2009.91   141.8 1986.32   171.6 1970.64
   245.5 1927.88   262.2 1919.34   301.8 1895.81  325.261886.063   345.3 1879.68
   374.3 1879.92     384 1873.04  388.471872.576   398.6 1872.85   404.6 1871.93
   413.2 1870.94   416.8 1871.59  433.421877.057   442.4 1882.27   452.1 1889.46
   461.8  1900.8   466.7 1905.44   500.4  1930.8   511.9 1937.99   603.9 1987.92
   687.9 2035.32   713.3 2050.87   764.9 2078.84     784    2091   795.6 2094.91
#Mann= 6 ,-1 , 0
       0      .1       0  325.26    .055       0  388.47     .06       0
   404.6    .045       0   416.8     .06       0  433.42      .1       0
Bank Sta=404.6,416.8
XS Rating Curve= 0 ,0
Exp/Cntr=0.3,0.1

Type RM Length L Ch R = 1 ,3202    ,152.8,148.8,145.7
XS GIS Cut Line= 4
     2445619.031       595307.412445748.89933455595627.521790082
2445817.04487371595735.2752205312446040.91780066595966.546836363
#Sta/Elev= 30
       0 2018.44    20.6 2009.43    37.9 2003.33   128.5 1965.99   179.7 1946.94
   216.5  1931.3   236.4 1923.77   275.6 1904.89   309.8 1888.79   331.4 1876.08
   353.7 1874.78   367.9 1869.51   377.5 1867.33   410.4 1867.28   419.9 1864.95
   424.6 1864.46   431.11864.935   438.3 1866.82   443.6 1870.62   452.8 1879.02
   462.5 1890.06  468.131893.949     572 1938.64     611 1960.69  643.411981.119
   656.9 1989.76   681.3 2007.06  724.182033.371   750.2  2049.9   794.8  2073.8
#Mann= 7 ,-1 , 0
       0      .1       0   275.6     .06       0   419.9    .045       0
   431.1     .06       0  468.13      .1       0  643.41      .1       0
  724.18      .1       0
Bank Sta=419.9,431.1
XS Rating Curve= 0 ,0
Exp/Cntr=0.3,0.1

Type RM Length L Ch R = 1 ,3053    ,149.6,147.1,145.1
XS GIS Cut Line= 4
2445533.75531306595374.6513808262445620.48504628595702.214395041
2445689.20510512595771.0703557382445913.99822777596011.937790082
#Sta/Elev= 30
       0 2010.11    82.6 1980.76     157  1949.8   177.7 1942.58   248.7  1910.3
   301.9 1888.04  314.161881.143   330.8 1868.76     358  1865.7   363.7 1863.36
   374.1 1855.56   382.5 1854.19   389.31854.974   405.2 1858.27   418.3 1864.86
  429.181871.822   437.3 1875.98   451.7 1881.06   475.9 1892.76   495.4 1904.72
   504.2 1912.26   521.2 1922.36   560.8 1943.52     583 1956.77   615.8 1972.08
   632.2 1982.94   690.9  2009.3   705.1 2014.76     748 2038.46   765.6 2044.86
#Mann= 5 ,-1 , 0
       0      .1       0  314.16     .06       0   374.1    .045       0
   389.3     .06       0  429.18      .1       0
Bank Sta=374.1,389.3
XS Rating Curve= 0 ,0
Exp/Cntr=0.3,0.1

Type RM Length L Ch R = 1 ,2906    ,160.2,158.5,155.8
XS GIS Cut Line= 4
2445348.63517785595486.6163986772445526.21056231 595815.63062281
2445631.25107669595892.092003342     2445881.551596050.974957355
#Sta/Elev= 30
       0 1979.02    71.8 1951.25   148.5 1926.05   222.5 1896.04   269.6 1883.06
   295.3 1872.54   313.8 1866.63  347.741860.983     364 1860.24   372.9  1857.1
   393.5 1856.98   413.2 1851.26   442.9 1848.15   450.2 1846.69   455.9 1848.16
   461.7 1851.92   469.4 1859.82  477.191863.707   487.4 1865.83   497.3 1869.95
   568.7 1904.24   620.8 1926.71   639.7 1936.21  647.311942.392   663.4 1957.69
   677.6 1973.44   706.1 2001.67   734.5 2026.16   768.3 2041.29   800.3 2053.62
#Mann= 6 ,-1 , 0
       0      .1       0  347.74     .06       0   442.9    .045       0
   455.9     .06       0  477.19      .1       0  647.31      .1       0
Bank Sta=442.9,455.9
XS Rating Curve= 0 ,0
Exp/Cntr=0.3,0.1

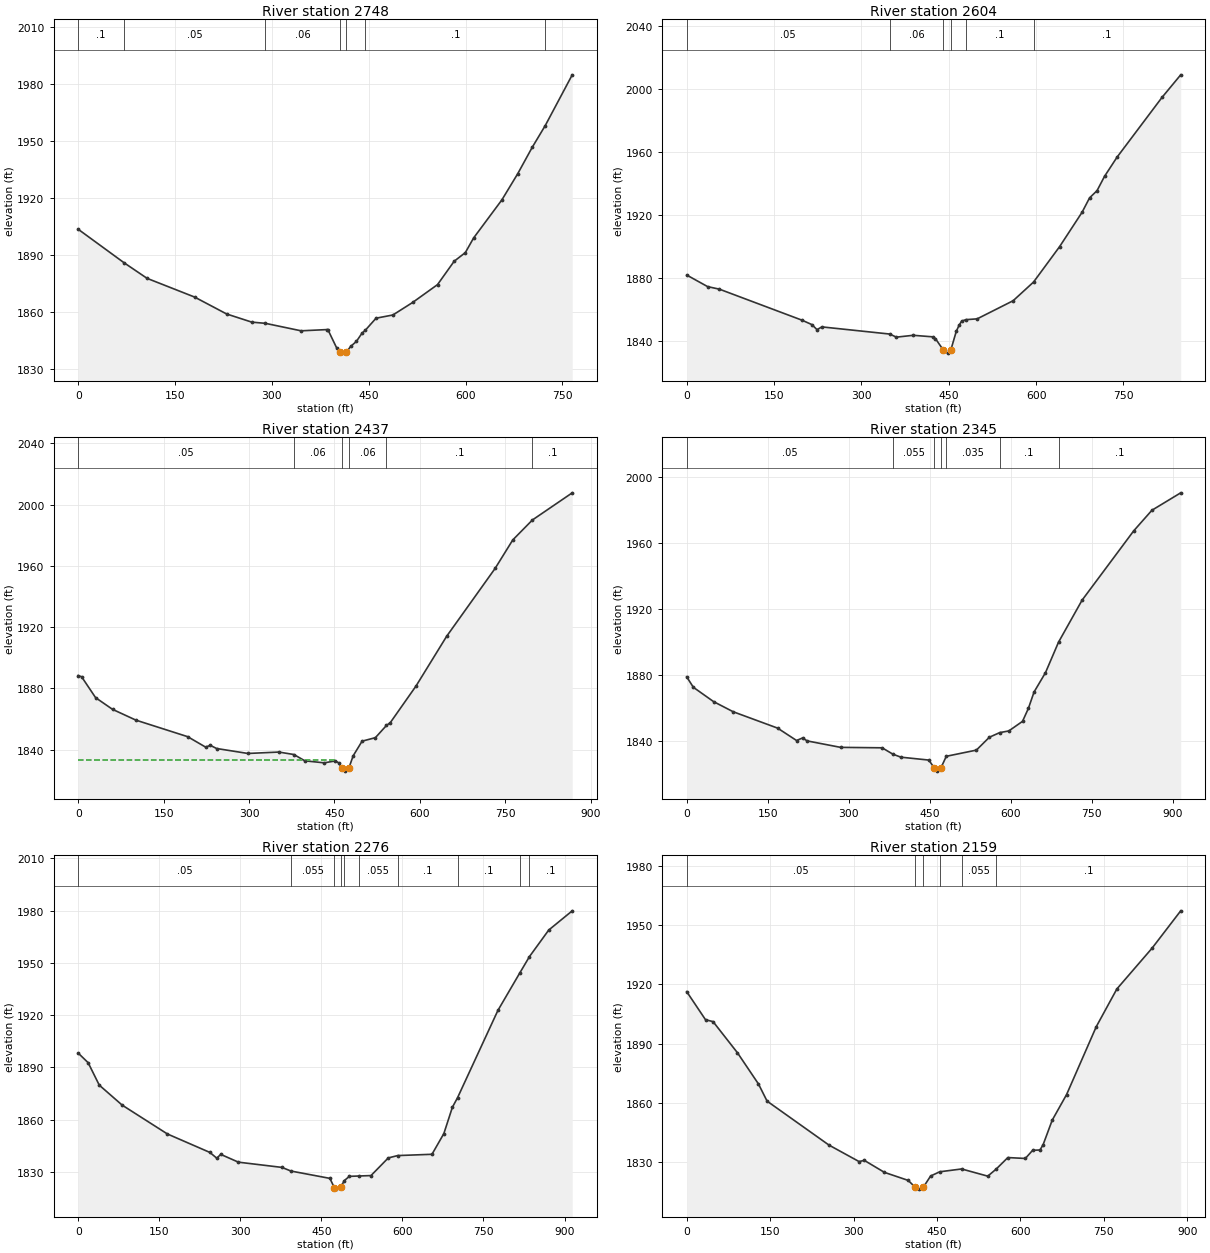
Type RM Length L Ch R = 1 ,2748    ,143,143.8,144.8
XS GIS Cut Line= 4
2445217.33693587595675.8121104122445411.05025983595945.096455537
2445552.84268528596006.2955299542445811.65321355596110.717380826
#Sta/Elev= 30
       0 1903.32    71.11885.687   106.7  1877.5   180.1 1867.69   229.9 1858.76
   268.9 1854.47  289.831853.849   345.2 1849.91   385.5 1850.56   387.3 1850.09
   400.3  1840.9   404.7 1838.83   411.1 1838.17   415.41838.793   422.1 1841.73
   430.8 1844.31   439.5 1848.64  444.721850.222   461.3 1856.55   487.4 1858.24
   517.9 1864.81   556.5 1874.21   582.3 1886.51   599.6 1891.06   612.5  1898.8
   656.2 1918.79   680.8 1932.59   703.1 1946.39   723.41957.905   765.2 1984.59
#Mann= 7 ,-1 , 0
       0      .1       0    71.1     .05       0  289.83     .06       0
   404.7    .045       0   415.4     .06       0  444.72      .1       0
   723.4      .1       0
Bank Sta=404.7,415.4
XS Rating Curve= 0 ,0
Exp/Cntr=0.3,0.1

Type RM Length L Ch R = 1 ,2604    ,164.3,166.9,170.7
XS GIS Cut Line= 4
     2445089.672      595848.994 2445404.5348043596093.467516033
2445491.47959636596137.544359045     2445820.025       596264.72
#Sta/Elev= 30
       0 1881.96      36  1874.6    56.2 1872.99     198 1853.31   215.1 1850.49
   223.7 1847.33   232.2 1849.05  348.811844.509     360 1842.55     389 1843.72
   422.8 1842.74   427.2  1841.6   440.7 1834.38   448.1 1832.41   453.8 1834.65
   462.9 1846.17   467.6 1849.96   472.1 1852.68  479.521853.651   498.8 1854.15
   560.6 1865.66  595.691877.525   640.4 1899.98     679 1921.79   691.9 1930.95
   704.7  1935.5   717.6 1944.61     739 1956.72   816.2 1994.64   848.4    2009
#Mann= 6 ,-1 , 0
       0     .05       0  348.81     .06       0   440.7    .045       0
   453.8     .06       0  479.52      .1       0  595.69      .1       0
Bank Sta=440.7,453.8
XS Rating Curve= 0 ,0
Exp/Cntr=0.3,0.1

Type RM Length L Ch R = 1 ,2437    ,82.8,91.6,101.1
XS GIS Cut Line= 4
      2445062.55      595881.7062445285.23143635596188.680266484
2445392.58513521596289.599846942     2445645.815      596517.945
#Sta/Elev= 30
       0 1888.37     5.9 1887.59    30.5 1873.93    60.2 1866.31   101.4 1859.24
   192.1 1848.46   223.6 1841.65   232.1 1842.76     243 1840.72     298 1837.48
   352.4  1838.4  378.65  1836.8     398 1832.67     432 1831.36   451.8 1832.62
   457.7 1831.26   463.5 1827.81   468.8 1825.94   475.2 1827.88   482.9 1835.98
   498.5 1845.51   521.9 1847.81  541.341855.795     548 1857.59   593.2 1881.53
     647 1914.02   732.1 1958.36   763.2    1977   797.61990.013   867.6 2007.76
#Mann= 6 ,-1 , 0
       0     .05       0  378.65     .06       0   463.5    .045       0
   475.2     .06       0  541.34      .1       0   797.6      .1       0
#XS Ineff= 2 , 0
           451.8 1832.98
Permanent Ineff=
       F       F
Bank Sta=463.5,475.2
XS Rating Curve= 0 ,0
Exp/Cntr=0.5,0.3

Type RM Length L Ch R = 1 ,2345    ,69.8,69,68.5
XS GIS Cut Line= 4
 2445070.5525685595904.8603248732445278.57072161596219.354870696
2445277.74764572596456.6201977332445472.74260361596684.594548741
#Sta/Elev= 30
       0 1878.88    12.3 1872.55    49.8 1863.85    86.2 1857.69   168.2 1847.79
   203.3 1840.27   214.4  1841.8     223 1840.02   284.8 1836.11   361.7 1835.84
  381.681831.962   396.5 1830.15   448.1  1828.4  458.22  1823.6   464.1 1821.69
   470.3 1823.54  480.441830.687   536.1 1834.44   560.2 1842.26  579.191845.044
   596.1 1846.07   621.5 1851.89   632.4 1859.77   642.9 1869.72     664 1881.42
  688.181899.944   731.7 1925.39   827.2 1967.43     861 1979.97   914.3 1990.54
#Mann= 7 ,-1 , 0
       0     .05       0  381.68    .055       0  458.22    .045       0
   470.3    .055       0  480.44    .035       0  579.19      .1       0
  688.18      .1       0
Bank Sta=458.22,470.3
XS Rating Curve= 0 ,0
Exp/Cntr=0.5,0.3

Type RM Length L Ch R = 1 ,2276    ,119.6,117.9,116.4
XS GIS Cut Line= 4
2445004.61722844595903.1696751272445212.63538155 596217.66422095
2445211.81230566596454.9295479872445406.80726355596682.903898995
#Sta/Elev= 30
       0 1898.12    18.3 1892.64    38.9 1879.76    81.3 1868.28     165 1851.72
   243.7 1841.11   256.4 1837.81   263.7 1840.01   296.4 1835.53   377.1 1832.52
  393.621830.438   465.8 1826.22   473.8 1820.97   477.8 1820.05   485.8 1821.15
  492.381824.929   501.8 1827.39  519.481827.588   541.8 1827.83   573.8 1837.96
  591.13 1839.31   654.7 1840.05   676.7 1851.96   692.5 1867.08  702.041872.541
   776.7 1922.64  816.691943.875  835.151953.565   870.8 1968.79   914.3 1979.82
#Mann= 10 ,-1 , 0
       0     .05       0  393.62    .055       0   473.8    .045       0
   485.8    .055       0  492.38    .035       0  519.48    .055       0
  591.13      .1       0  702.04      .1       0  816.69      .1       0
  835.15      .1       0
Bank Sta=473.8,485.8
XS Rating Curve= 0 ,0
Exp/Cntr(USF)=0,0
Exp/Cntr=0.5,0.3

Type RM Length L Ch R = 1 ,2159    ,171.3,165.3,158.8
XS GIS Cut Line= 4
2444912.54343659595940.5478853152445089.91003744596273.892898378
2445098.90899275596349.6563486542445280.42092723 596744.22326753
#Sta/Elev= 30
       0 1916.37    33.8 1902.15    47.4 1901.18    91.3 1885.38     129 1869.61
   144.5 1860.91   255.8 1838.64   309.9 1830.29   319.3  1830.9   355.5 1824.82
   398.2 1820.75   410.5 1817.38   418.4 1816.33   425.21817.188   438.5 1822.97
  454.841825.112  494.271826.543   541.3  1822.9  556.231826.439   577.4 1832.32
   608.8 1831.86     622    1836   635.2 1836.16   640.8 1838.84   657.2 1851.28
     683 1864.24   736.4 1898.64   773.4 1917.73   836.8 1938.43   888.2 1957.31
#Mann= 6 ,-1 , 0
       0     .05       0   410.5    .045       0   425.2     .05       0
  454.84     .06       0  494.27    .055       0  556.23      .1       0
Bank Sta=410.5,425.2
XS Rating Curve= 0 ,0
Exp/Cntr=0.3,0.1

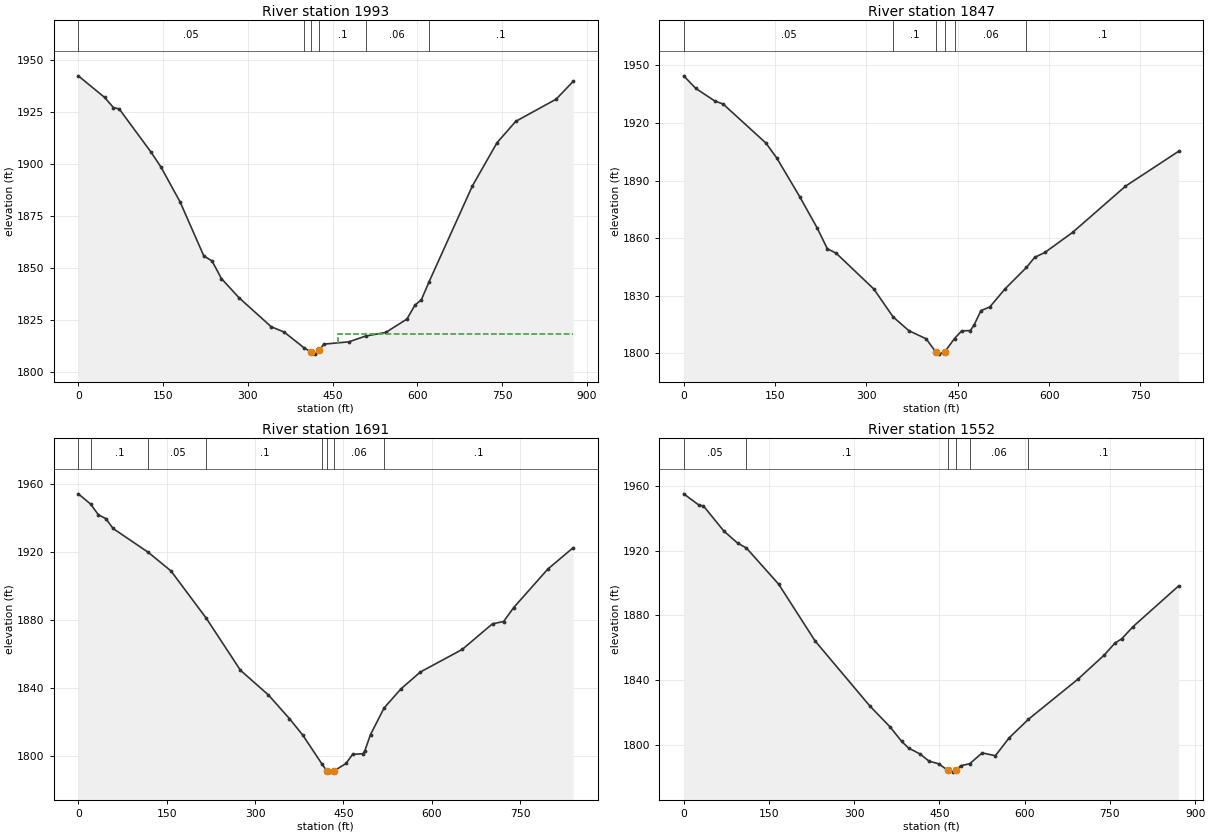
Type RM Length L Ch R = 1 ,1993    ,143.2,146.4,149.1
XS GIS Cut Line= 4
     2444702.406      596062.0142444937.48753276596354.111301091
2445013.01795576596459.3596698572445243.83770671596749.908077223
#Sta/Elev= 30
       0 1942.18    46.7 1931.79    62.1 1926.96    72.4  1926.3   128.9 1905.48
   146.3 1898.38   180.2 1881.62     222 1855.78   236.7 1853.29   253.3 1844.83
   284.5 1835.63   341.4 1821.73   364.2 1819.19   398.81811.766   411.71809.622
   419.6 1808.59   426.61810.576   434.3 1813.38   478.9  1814.5   508.21817.254
   544.1 1819.01   581.4 1825.41   595.6 1832.09     607 1834.68  620.411843.181
   697.3 1889.33   740.8 1910.05   773.9  1920.3   845.5 1930.98   875.6 1939.51
#Mann= 6 ,-1 , 0
       0     .05       0   398.8      .1       0   411.7    .045       0
   426.6      .1       0   508.2     .06       0  620.41      .1       0
#XS Ineff= 2 , 0
                          460.11         1818.23
Permanent Ineff=
       F       F
Bank Sta=411.7,426.6
XS Rating Curve= 0 ,0
Exp/Cntr=0.3,0.1

Type RM Length L Ch R = 1 ,1847    ,156.5,156.3,154.2
XS GIS Cut Line= 4
      2444665.78      596084.4292444834.49045944596439.489687206
2444861.14431067596506.9160637752445112.07056787 596746.61436271
#Sta/Elev= 30
       0 1944.56    19.9 1937.99    50.9 1931.47    64.8 1929.86     135 1909.54
   152.7 1901.81   190.9 1881.38   219.2  1865.3   235.9 1854.45   250.2 1852.23
   312.2 1833.52  343.781819.018   369.7 1811.84   398.1 1807.59   413.91800.769
   419.7 1799.62   428.9 1800.93  444.631807.751   456.4 1811.71   470.6 1811.91
   476.4 1814.55     488 1822.26   502.7 1824.22   527.8 1833.67  562.731844.752
   576.2 1849.99   593.2  1852.6   638.5    1863   725.4 1887.09   812.6 1905.26
#Mann= 6 ,-1 , 0
       0     .05       0  343.78      .1       0   413.9    .045       0
   428.9      .1       0  444.63     .06       0  562.73      .1       0
Bank Sta=413.9,428.9
XS Rating Curve= 0 ,0
Exp/Cntr=0.3,0.1

Type RM Length L Ch R = 1 ,1691    ,136.6,138.3,139.4
XS GIS Cut Line= 4
     2444584.733      596113.4952444695.36238222596504.711536661
2444729.21366948596565.210998254     2444920.963      596874.781
#Sta/Elev= 30
       0 1954.47   20.761948.488    34.2 1942.09    46.7 1939.86    59.1 1934.02
  119.011919.901   157.4 1908.96  217.271881.082   275.3 1850.38   322.7 1835.85
   358.3 1821.92     381 1812.16   414.2 1794.82   422.2 1790.87   426.8 1790.32
   433.3 1790.85   454.3 1795.41   465.6 1800.78   483.2 1801.21   486.1 1802.68
     496 1812.48  519.011828.146   547.8 1839.47   580.7 1849.39   651.7 1862.69
   703.1 1877.84   721.9 1879.13   738.8 1887.29   796.9 1910.05     840  1922.7
#Mann= 8 ,-1 , 0
       0     .05       0   20.76      .1       0  119.01     .05       0
  217.27      .1       0   414.2     .06       0   422.2    .045       0
   433.3     .06       0  519.01      .1       0
Bank Sta=422.2,433.3
XS Rating Curve= 0 ,0
Exp/Cntr=0.3,0.1

Type RM Length L Ch R = 1 ,1552    ,122.6,132.2,140.8
XS GIS Cut Line= 4
     2444547.565      596127.7212444577.34002438596560.608766585
2444615.99446724596657.911011703     2444787.338      596942.571
#Sta/Elev= 30
       0 1955.19    26.7 1948.24    34.8 1947.68    70.8 1932.12    94.9 1924.72
  110.191921.752   167.1 1899.35   231.2 1864.26   327.4 1824.13   363.5 1811.01
   383.5 1802.21   395.6 1798.07   415.6 1794.48   431.7 1789.97   448.7 1788.35
   464.71784.291   474.5 1783.19   479.11784.198   487.4 1787.16  503.221788.358
   525.2 1795.08   548.5 1793.33   572.5 1804.31  606.691815.876   693.2 1840.49
   739.8 1855.45     759 1862.98   770.7 1865.55   790.9 1873.18   870.9 1898.25
#Mann= 6 ,-1 , 0
       0     .05       0  110.19      .1       0   464.7    .045       0
   479.1      .1       0  503.22     .06       0  606.69      .1       0
Bank Sta=464.7,479.1
XS Rating Curve= 0 ,0
Exp/Cntr=0.3,0.1