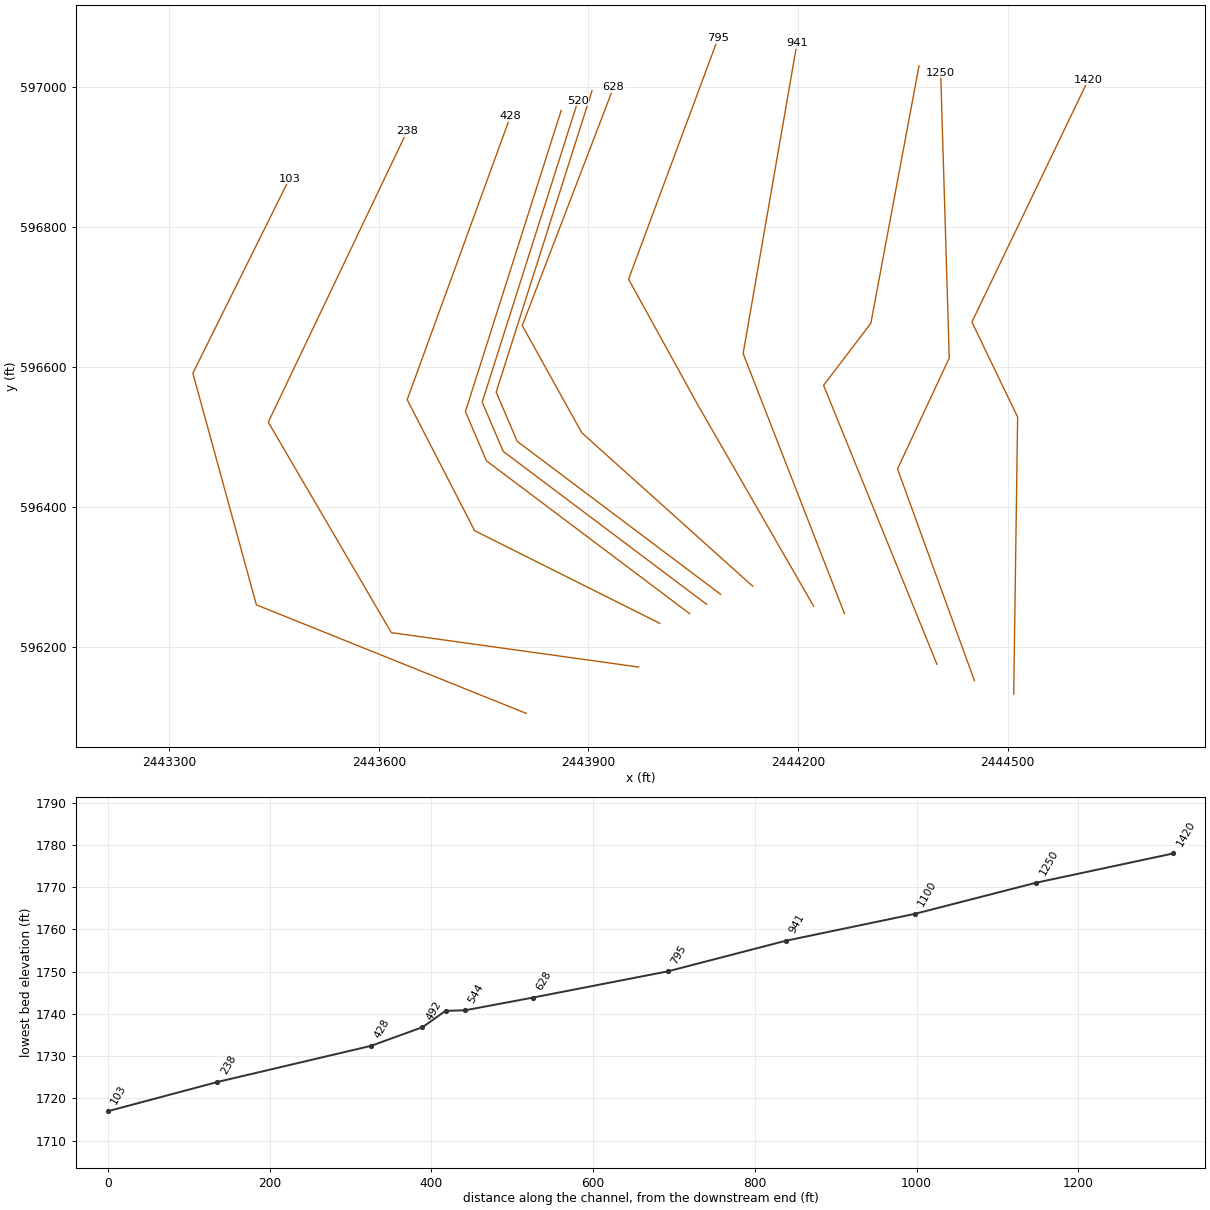
HEC-RAS study PROPSTRN.prj: PROPSTRN

--- PROPSTRN.g01 (geometry) --- (continued)

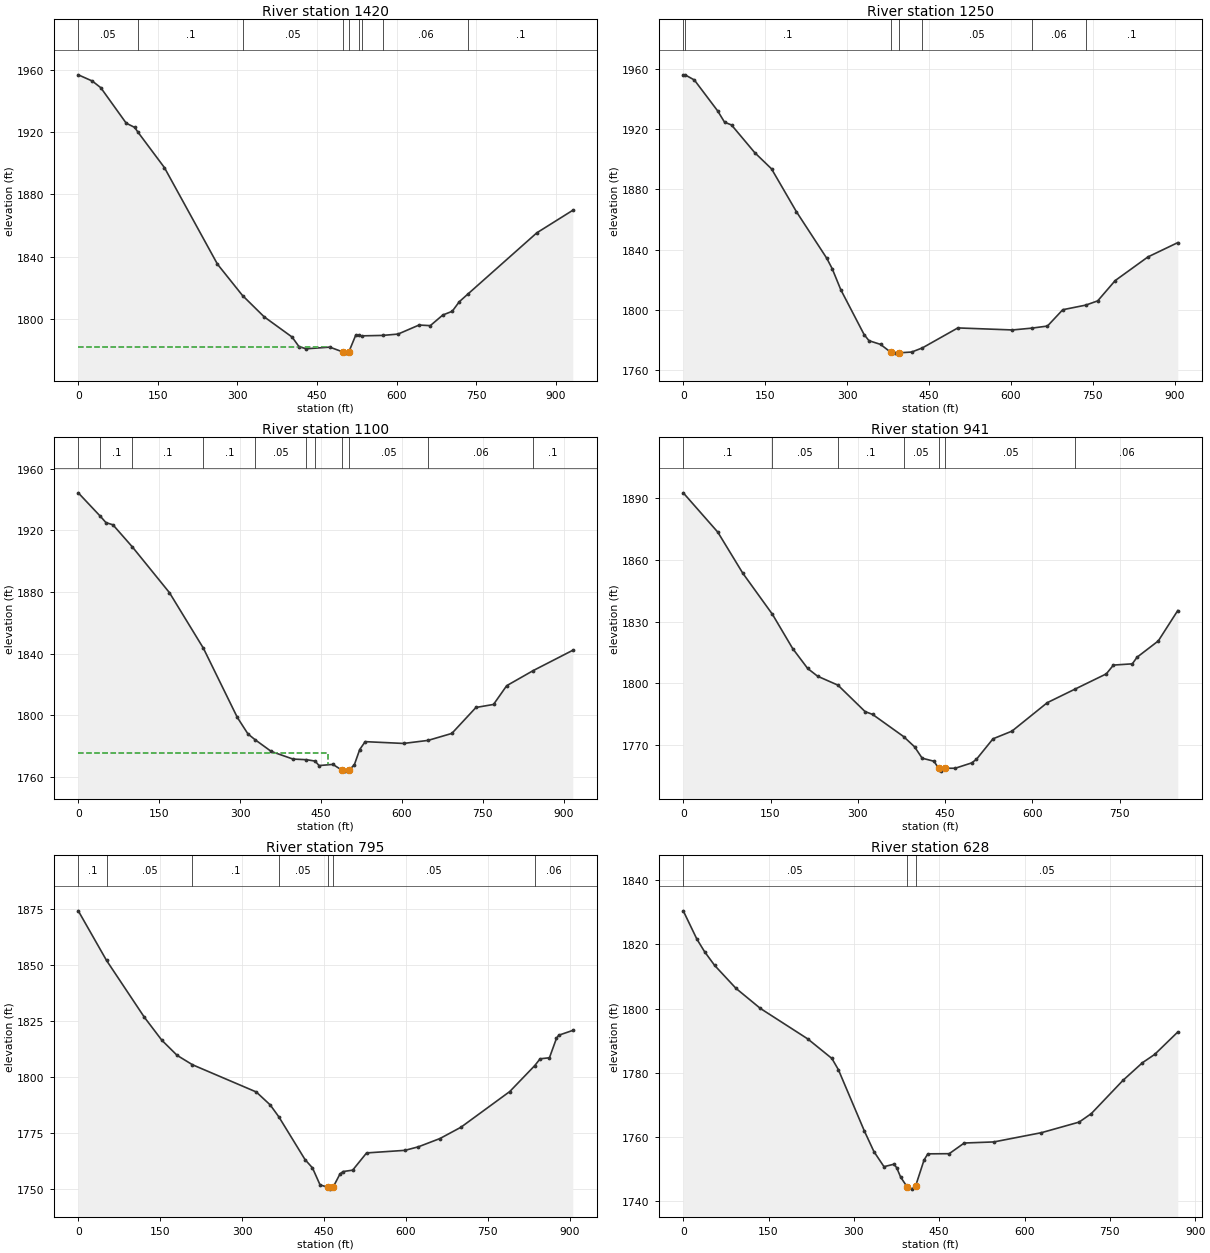
Type RM Length L Ch R = 1 ,1420    ,180.9,169.9,157.6
XS GIS Cut Line= 4
     2444508.861      596131.9732444514.44285823596528.393144899
2444448.97992278 596664.366702812444615.67342122597011.071459438
#Sta/Elev= 30
       0 1956.76    26.4 1952.78    42.4  1948.5    90.4 1925.69   106.4 1922.97
  112.631919.878   162.4 1897.16   262.4  1835.1  309.611814.978   350.4 1801.29
   403.1 1788.28   416.1 1782.12   429.7 1780.74   474.1 1781.82   498.51778.749
   505.2 1777.96   510.21778.879   522.9  1789.4  528.861789.327  534.281789.057
   573.81789.344   602.8  1790.2   642.4 1796.01   663.6 1795.62   687.1 1802.44
   704.9 1804.84   718.2 1810.97  735.251816.162   864.4 1855.26   932.1 1869.72
#Mann= 9 ,-1 , 0
       0     .05       0  112.63      .1       0  309.61     .05       0
   498.5    .045       0   510.2     .05       0  528.86     .06       0
  534.28     .05       0   573.8     .06       0  735.25      .1       0
#XS Ineff= 2 , 0
          473.69 1781.88
Permanent Ineff=
       F       F
Bank Sta=498.5,510.2
XS Rating Curve= 0 ,0
Exp/Cntr=0.3,0.1

Type RM Length L Ch R = 1 ,1250    ,152.5,150,147
XS GIS Cut Line= 4
2444452.52558737596151.3336138842444342.51764222596454.147891833
2444416.55747114596612.870942281     2444404.293      597020.842
#Sta/Elev= 30
       0  1956.3       41956.137    20.3 1952.87    62.8 1932.38    75.6 1924.78
    88.4  1922.9   130.9 1904.49   161.6 1893.72   207.1 1865.24   262.8 1834.16
   272.7 1827.26   288.5 1813.21   331.2 1783.36   340.1  1779.3   361.2 1776.84
   380.31771.519   388.6 1771.02   394.91771.206   418.4 1771.75  438.061774.538
   502.8  1787.8   602.8 1786.45  637.841787.644   666.9 1789.04   694.9 1799.91
  737.051802.988   758.9  1805.8   790.9 1819.31   850.9 1835.07   905.5 1844.58
#Mann= 7 ,-1 , 0
       0     .05       0       4      .1       0   380.3    .045       0
   394.9      .1       0  438.06     .05       0  637.84     .06       0
  737.05      .1       0
Bank Sta=380.3,394.9
XS Rating Curve= 0 ,0
Exp/Cntr=0.3,0.1

Type RM Length L Ch R = 1 ,1100    ,153.7,159.5,165
XS GIS Cut Line= 4
 2444398.8506685596174.7832277682444236.66631382596573.805915239
2444304.30454446596662.554776132     2444373.251      597030.742
#Sta/Elev= 30
       0 1944.31   41.131929.016    51.4 1924.96    64.3 1923.55   100.4 1909.16
   169.1  1879.5  232.141843.363   294.9 1798.53   314.7 1787.77  327.841784.055
   357.9 1776.42   398.1 1771.48  423.151771.067  439.091770.176   446.5 1767.25
   472.1 1768.03   488.51764.359     495 1763.65   502.31764.373   511.9 1767.76
   521.9 1777.68     532 1782.79   603.1 1781.62  648.641783.602   692.7 1788.13
   737.4 1804.97     770 1806.94   794.4 1819.11  843.791828.956   916.9 1842.09
#Mann= 11 ,-1 , 0
       0      .1       0   41.13      .1       0   100.4      .1       0
  232.14      .1       0  327.84     .05       0  423.15      .1       0
  439.09     .05       0   488.5    .045       0   502.3     .05       0
  648.64     .06       0  843.79      .1       0
#XS Ineff= 2 , 0
          463.28 1775.57
Permanent Ineff=
       F       F
Bank Sta=488.5,502.3
XS Rating Curve= 0 ,0
Exp/Cntr=0.3,0.1

Type RM Length L Ch R = 1 ,941     ,139.9,145.7,153.8
XS GIS Cut Line= 3
2444266.56703511596247.0894711412444121.48030499596619.344914975
     2444198.588       597063.25
#Sta/Elev= 30
       0 1892.71    59.3 1873.61   102.3 1853.62  153.411833.546   188.1 1816.94
   213.9 1807.24     231 1803.47  265.941799.121   312.6 1786.26   325.5 1784.89
  378.69 1774.13   397.6 1769.14   410.7 1763.59     431  1762.1   439.1 1758.65
   443.2 1757.29   450.61758.693   467.5 1758.69   495.9  1761.3   504.1 1763.08
   532.5 1773.02     565 1776.74   625.8  1790.6  674.14 1797.29   727.3 1804.62
   739.5 1808.89     772  1809.5   780.1 1812.71   816.6 1820.63   850.1 1835.42
#Mann= 7 ,-1 , 0
       0      .1       0  153.41     .05       0  265.94      .1       0
  378.69     .05       0   439.1    .045       0   450.6     .05       0
  674.14     .06       0
Bank Sta=439.1,450.6
XS Rating Curve= 0 ,0
Exp/Cntr=0.3,0.1

Type RM Length L Ch R = 1 ,795     ,167.3,167.2,167.1
XS GIS Cut Line= 4
2444222.48680344596257.5260889262444055.45793448596547.811439933
2443957.46425921 596725.67956033 2444085.5966685597070.313857256
#Sta/Elev= 30
       0 1874.19    51.81852.056   120.9 1826.78     153 1816.49     181 1809.74
  209.191805.535     326  1793.4   351.5 1787.64  367.321782.328   415.4 1763.22
     429 1759.52   442.8 1751.98   456.5 1750.92   461.1 1750.06   467.3 1751.18
   479.4 1756.84   484.9 1757.89   502.6 1758.53   528.1 1766.21   598.4 1767.36
   623.1 1768.95   662.4 1772.62   700.8 1777.65   790.4  1793.6  836.241805.198
   845.9 1808.19     863 1808.65   875.8 1817.27   880.1 1818.71   905.7 1820.85
#Mann= 7 ,-1 , 0
       0      .1       0    51.8     .05       0  209.19      .1       0
  367.32     .05       0   456.5    .045       0   467.3     .05       0
  836.24     .06       0
Bank Sta=456.5,467.3
XS Rating Curve= 0 ,0
Exp/Cntr=0.3,0.1

Type RM Length L Ch R = 1 ,628     ,85.1,83.4,82
XS GIS Cut Line= 4
2444135.19970326596286.3220109892443890.49957624596505.899363053
2443805.27306385596659.3070853682443935.95371619597000.213134956
#Sta/Elev= 30
       0 1830.45      24 1821.63    37.6  1817.7    55.1 1813.48    92.7 1806.32
   135.7 1800.06   218.8  1790.6   261.3 1784.51   272.7 1781.03   318.4 1761.94
   335.2 1755.53   352.9 1750.83   370.5  1751.6   375.1 1750.54   382.3 1747.55
   393.4  1744.6   402.5 1743.84   408.61744.876   423.4 1752.92     430 1754.82
   467.6 1754.87     494 1758.19   546.1 1758.53   629.8 1761.41     696  1764.7
   717.4 1767.34   773.1 1777.69   807.4 1783.19   828.8 1785.76   869.4 1792.73
#Mann= 3 ,-1 , 0
       0     .05       0   393.4    .045       0   408.6     .05       0
Bank Sta=393.4,408.6
XS Rating Curve= 0 ,0
Exp/Cntr(USF)=0,0
Exp/Cntr=0.3,0.1

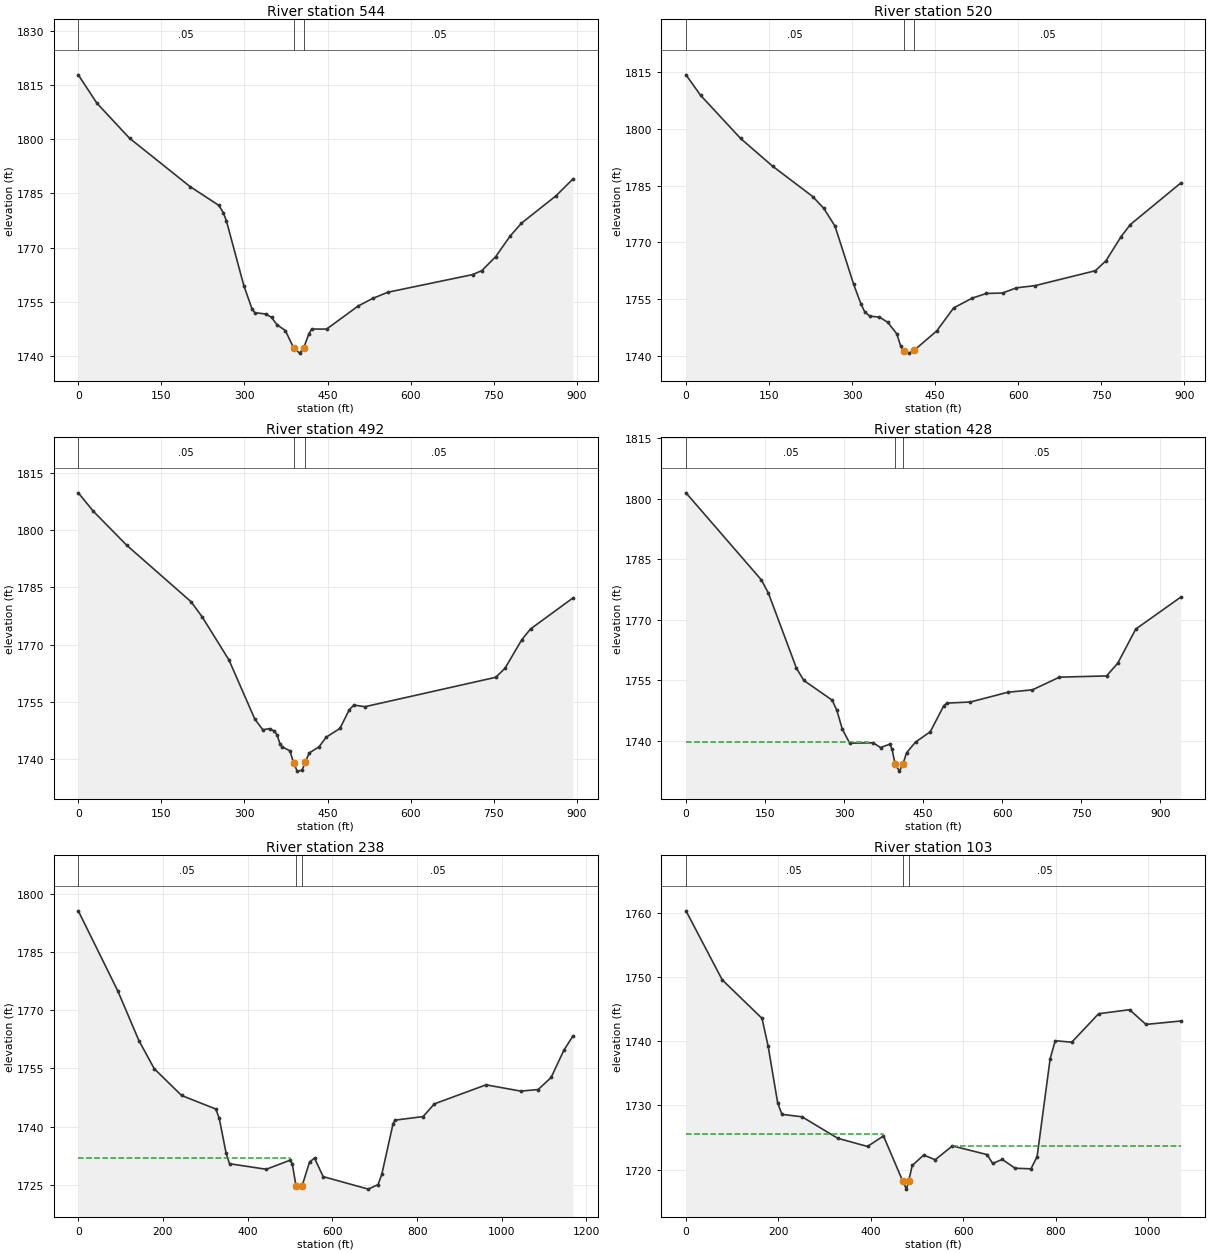
Type RM Length L Ch R = 1 ,544     ,24.1,24.2,24.1
XS GIS Cut Line= 4
2444089.17248943596274.7994791792443798.00503331  596493.6446962
2443767.94903784596564.0884355842443905.07951717596995.204120617
#Sta/Elev= 30
       0 1817.79    33.7 1809.94    92.5 1800.27   201.8  1786.9   253.9 1781.69
   261.8 1779.69   267.5 1777.41   298.9 1759.52   313.9    1753   318.9 1752.03
   338.8 1751.66     349 1750.72     359 1748.67   373.9  1747.1     389 1742.23
   399.8 1740.85   407.3  1742.4   416.4 1746.22   421.6 1747.51   448.4  1747.5
     505 1753.84   531.3 1755.96   559.1 1757.69   711.9 1762.56   728.6 1763.66
   753.8 1767.54   779.3 1773.13     800 1776.75   862.9 1784.39   893.2 1789.01
#Mann= 3 ,-1 , 0
       0     .05       0     389    .045       0   407.3     .05       0
Bank Sta=389,407.3
XS Rating Curve= 0 ,0
Exp/Cntr(USF)=0,0
Exp/Cntr=0.5,0.3

Type RM Length L Ch R = 1 ,520     ,28.4,28.5,27.9
XS GIS Cut Line= 4
2444069.13057811596260.4838282352443777.96312199596479.329045256
2443747.90712651 596549.772784642443885.03760585596980.888469673
#Sta/Elev= 30
       0 1814.24    26.3 1808.84    98.7 1797.42   156.3 1790.12   228.8 1782.09
   248.8 1778.97   269.1 1774.26   302.7 1758.93     316 1753.67   322.7 1751.64
   331.9  1750.5   349.3 1750.23   364.2 1748.87   380.6 1745.81   387.7 1742.58
   393.3 1741.34   402.9 1740.72   412.1 1741.49   452.7 1746.58   483.4 1752.68
     517 1755.26   542.2 1756.48   571.5  1756.6   596.7 1757.97   630.3 1758.55
   739.3  1762.5   758.4 1765.14   785.6 1771.49   802.4  1774.7   893.2 1785.64
#Mann= 3 ,-1 , 0
       0     .05       0   393.3    .045       0   412.1     .05       0
Bank Sta=393.3,412.1
XS Rating Curve= 0 ,0
Exp/Cntr(USF)=0,0
Exp/Cntr=0.5,0.3

Type RM Length L Ch R = 1 ,492     ,62.5,63.6,65.6
XS GIS Cut Line= 4
2444045.12752617596246.9168858352443753.96007005596465.762102856
2443723.90407458 596536.205842242443861.03455391596967.321527273
#Sta/Elev= 30
       0 1809.76    27.4  1804.9    87.4 1796.04   203.8 1781.21   223.8 1777.24
   272.1 1765.97   318.6 1750.53   333.1 1747.69   345.3 1747.98   353.9 1747.36
   358.8 1746.42   364.2 1743.99   367.5 1743.29   382.3 1742.14   388.7 1739.02
   395.3 1736.85   404.1 1737.09   409.61739.177   417.1 1741.63   434.5 1743.18
   447.6 1745.74   472.5 1748.05   489.3 1752.94   497.6 1754.15   517.6 1753.73
   753.7 1761.43   770.5 1763.79     801 1771.33   816.6  1774.1   893.2 1782.22
#Mann= 3 ,-1 , 0
       0     .05       0   388.7    .045       0   409.6     .05       0
Bank Sta=388.7,409.6
XS Rating Curve= 0 ,0
Exp/Cntr(USF)=0,0
Exp/Cntr=0.5,0.3

Type RM Length L Ch R = 1 ,428     ,188.8,189.9,190.1
XS GIS Cut Line= 4
2444002.24100361596233.1745233822443737.09185393596365.749098222
2443640.50180655596553.2474254962443788.22776137596958.546840006
#Sta/Elev= 30
       0 1801.51   143.1 1779.89   156.5 1776.58   209.6 1757.99   223.6 1754.95
   277.3 1750.06   286.2 1747.57   296.4 1742.94   310.6 1739.38   355.1 1739.47
   369.1  1738.3   387.1 1739.14   391.1 1737.81     397 1734.11   405.1 1732.44
   411.9 1734.26   411.9 1734.27   418.6 1737.01   435.6 1739.65   463.6 1742.22
   489.1 1748.66   494.8 1749.32   539.8  1749.6   610.7 1752.02   657.5 1752.62
   708.6 1755.76     798 1756.07   819.3 1759.23   853.4 1767.69   938.7 1775.61
#Mann= 3 ,-1 , 0
       0     .05       0     397    .045       0   411.9     .05       0
#XS Ineff= 2 , 0
          346.14 1739.61
Permanent Ineff=
       F       F
Bank Sta=397,411.9
XS Rating Curve= 0 ,0
Exp/Cntr(USF)=0,0
Exp/Cntr=0.3,0.1

Type RM Length L Ch R = 1 ,238     ,137,135.6,133.4
XS GIS Cut Line= 4
2443971.93824365596170.6750809572443617.77473657596219.917065898
2443441.63994429596521.0507430342443640.50180655596937.713692532
#Sta/Elev= 30
       0 1795.54    93.5 1774.87   143.2 1762.13   179.4 1754.89     244    1748
   324.8 1744.51   332.9 1742.09     349 1733.17   357.1 1730.43   443.9    1729
   499.4 1731.31   505.2 1730.48     514 1724.79   528.6 1724.79   546.1 1730.86
   557.8 1731.88   578.2 1727.11   684.8 1723.89   707.9 1725.06   716.9 1727.79
   743.3 1740.74   747.8 1741.65   814.2 1742.57   840.8 1745.84   962.9 1750.74
  1044.7 1749.13  1085.9 1749.53  1116.5 1752.64  1146.6 1759.65  1168.1 1763.34
#Mann= 3 ,-1 , 0
       0     .05       0     514    .045       0   528.6     .05       0
#XS Ineff= 2 , 0
          499.59 1731.88  557.14          1731.7
Permanent Ineff=
       F       F
Bank Sta=514,528.6
XS Rating Curve= 0 ,0
Exp/Cntr(USF)=0,0
Exp/Cntr=0.3,0.1

Type RM Length L Ch R = 1 ,103     ,,,
XS GIS Cut Line= 4
2443810.95483134596104.3877935372443424.59464181 596259.68943835
2443333.68636192 596591.125875452443471.94270425596869.532482614
#Sta/Elev= 30
       0 1760.29    78.4 1749.55   164.6 1743.55   177.9  1739.2   198.4 1730.42
   207.7 1728.61   251.2 1728.23   328.4 1724.89     393 1723.61   427.5 1725.25
     469 1718.25   477.3 1716.97   482.3  1718.3   489.7 1720.65   514.6 1722.28
   539.5 1721.54   576.7  1723.7     652 1722.34   663.9 1720.96   684.6  1721.6
   712.5 1720.22   746.8 1720.13   760.1 1722.04   788.4  1737.3   799.4 1740.07
   835.1 1739.84   893.2 1744.27   960.2  1744.9   995.7 1742.61  1070.9 1743.14
#Mann= 3 ,-1 , 0
       0     .05       0     469    .045       0   482.3     .05       0
#XS Ineff= 2 , 0
          426.12 1725.59  575.51         1723.76
Permanent Ineff=
       F       F
Bank Sta=469,482.3
XS Rating Curve= 0 ,0
Exp/Cntr(USF)=0,0
Exp/Cntr=0.3,0.1
LCMann Table=0

Chan Stop Cuts=-1
Use User Specified Reach Order=0
Composite Channel Slope=5